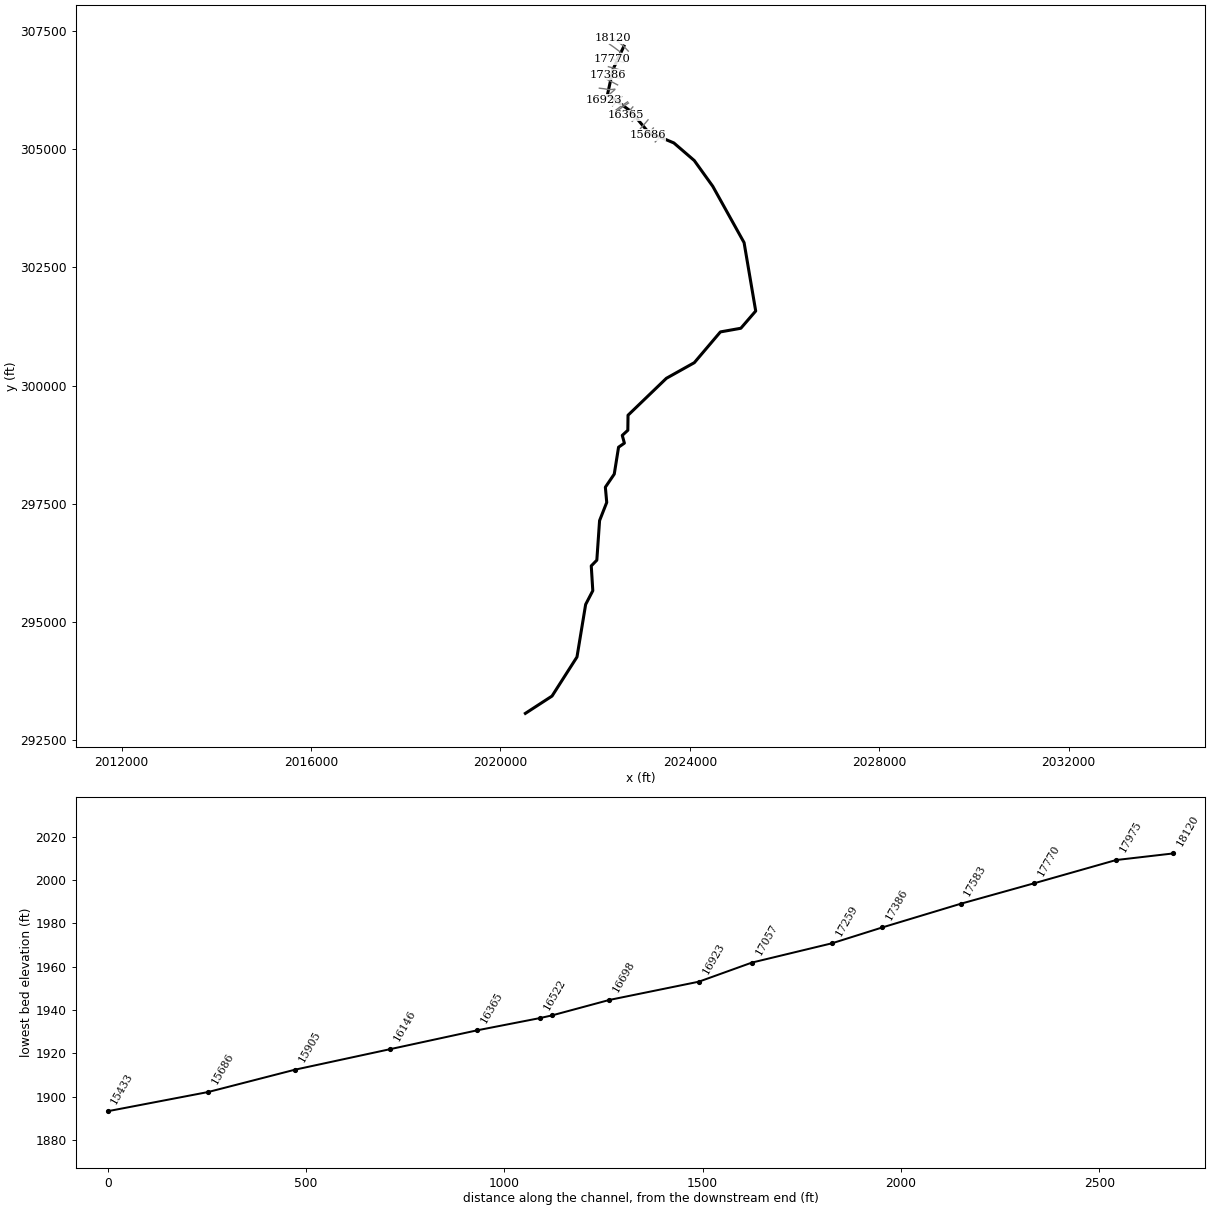
--- MILLCK.prj (project) ---

Proj Title=MILLCK
Current Plan=p01
Default Exp/Contr=0,0
English Units
Geom File=g01
Flow File=f01
Plan File=p01
BEGIN DESCRIPTION:
Stream Name: Mill Creek
Flood Zone: Detailed
Summers County, West Virginia
HEC-RAS Version: 5.0.7
Hydrology Method: Regression
Model Notes:
END DESCRIPTION:
DSS Export Rating Curves= 0
DSS Export Rating Curve Sorted= 0
DSS Export Volume Flow Curves= 0
DXF OffsetX= 0
DXF OffsetY= 0
DXF ScaleX= 0
DXF ScaleY= 0

--- MILLCK.p01 (plan) ---

Plan Title=Floodplain
Program Version=5.07
Short Identifier=Floodplain
Geom File=g01
Flow File=f01
Subcritical Flow
K Sum by GR= 0
Std Step Tol= 0.01
Critical Tol= 0.01
Num of Std Step Trials= 20
Max Error Tol= 0.3
Flow Tol Ratio= 0.001
Split Flow NTrial= 30
Split Flow Tol= 0.02
Split Flow Ratio= 0.02
Log Output Level= 0
Friction Slope Method= 1
Unsteady Friction Slope Method= 2
Unsteady Bridges Friction Slope Method= 1
Parabolic Critical Depth
Global Vel Dist= 0 , 0 , 0
Global Log Level= 0
CheckData=True
Encroach Param=-1 ,5,5, 2
Encroach River=MILLCK
Encroach Reach=Main
Encroach Node=18120
       1   119.2     161
Encroach Node=17975
       1   114.8   145.3
Encroach Node=17770
       1    98.3   121.7
Encroach Node=17583
       1     121     165
Encroach Node=17386
       1    87.4   125.1
Encroach Node=17259
       1   92.79     124
Encroach Node=17057
       1     139   174.2
Encroach Node=16923
       1     153   189.8
Encroach Node=16698
       1     112     154
Encroach Node=16554
       1      95     142
Encroach Node=16522
       1    96.6   138.5
Encroach Node=16365
       1    77.2   122.2
Encroach Node=16146
       1     138   188.8
Encroach Node=15905
       1   106.3     154
Encroach Node=15686
       1   119.3   147.5
Encroach Node=15433
       1    76.4     105
Encroach Node=15336
       1     109  140.75
Encroach Node=15299
       1   108.1     139
Encroach Node=15134
       1    50.4    84.6
Encroach Node=14934
       1      55    82.5
Encroach Node=14725
       1    91.1   117.9
Encroach Node=14542
       1    60.4      84
Encroach Node=14434
       1   103.4   127.7
Encroach Node=14396
       1   116.3   140.6
Encroach Node=14250
       1     113   149.6
Encroach Node=14043
       1   112.5     154
Encroach Node=13816
       1   140.9     194
Encroach Node=13629
       1   150.6   190.1
Encroach Node=13543
       1     145   180.5
Encroach Node=13432
       1   169.8     200
Encroach Node=13285
       1   121.6     152
Encroach Node=13129
       1     124   150.6
Encroach Node=12899
       1   129.2     148
Encroach Node=12744
       1   216.7     249
Encroach Node=12510
       1     148   193.2
Encroach Node=12355
       1   134.1   169.1
Encroach Node=12190
       1     185   220.8
Encroach Node=11986
       1   199.5     233
Encroach Node=11770
       1   206.1   233.4
Encroach Node=11551
       1   150.8     193
Encroach Node=11351
       1   138.8     182
Encroach Node=11121
       1   236.1   277.5
Encroach Node=11029
       1   313.2   344.9
Encroach Node=10957
       1    98.3   143.6
Encroach Node=10844
       1   139.6   175.1
Encroach Node=10614
       1    94.5   131.9
Encroach Node=10355
       1    69.9   103.8
Encroach Node=10039
       1     135   179.7
Encroach Node=9854
       1    79.9   116.4
Encroach Node=9529
       1     116     152
Encroach Node=9323
       1    97.4     147
Encroach Node=9155
       1      52     115
Encroach Node=8968
       1     105   141.5
Encroach Node=8809
       1     109   146.4
Encroach Node=8555
       1   102.2   138.9
Encroach Node=8259
       1     114     169
Encroach Node=7876
       1     150  237.75
Encroach Node=7544
       1     222     262
Encroach Node=7222
       1     300     365
Encroach Node=7170
       1     300     366
Encroach Node=6950
       1     171     209
Encroach Node=6636
       1    85.1     135
Encroach Node=6316
       1   108.1   139.5
Encroach Node=5972
       1     121   156.4
Encroach Node=5675
       1   115.9     155
Encroach Node=5396
       1     153   208.7
Encroach Node=5191
       1   139.7     186
Encroach Node=4951
       1   137.5     194
Encroach Node=4748
       1     196   237.5
Encroach Node=4501
       1   185.9   219.2
Encroach Node=4287
       1     132     184
Encroach Node=4112
       1     173   215.8
Encroach Node=3872
       1   130.9   167.4
Encroach Node=3587
       1   206.9   249.9
Encroach Node=3388
       1   144.9  217.92
Encroach Node=3167
       1      97     141
Encroach Node=2892
       1   130.5   175.7
Encroach Node=2716
       1     155   196.2
Encroach Node=2492
       1   122.9   173.7
Encroach Node=2213
       1     103     141
Encroach Node=1940
       1      78   123.5
Encroach Node=1752
       1   111.3     146
Encroach Node=1497
       1     195   239.3
Encroach Node=1218
       1     234     299
Encroach Node=1090
       1   224.5     275
Encroach Node=890
       1   201.3   245.4
Encroach Node=639
       1   176.1   214.9
Encroach Node=318
       1   142.7   188.5
Encroach Node=0
       1  234.17     310
Mapping Interval=1HOUR
Computation Time Step Use Courant=        0
Computation Time Step Use Time Series=    0
Computation Time Step Count To Double=0
Computation Time Step Max Doubling=0
Computation Time Step Max Halving=0
Computation Time Step Residence Courant=0
Run HTab= 0
Run UNet= 0
Run Sediment= 0
Run PostProcess= 0
Run WQNet= 0
Run RASMapper= 0
UNET Theta= 0
UNET Theta Warmup= 0
UNET ZTol= 0
UNET ZSATol= 0
UNET MxIter= 0
UNET Max Iter WO Improvement= 0
UNET MaxInSteps= 0
UNET DtIC= 0
UNET DtMin= 0
UNET MaxCRTS= 0
UNET WFStab= 0
UNET SFStab= 0
UNET WFX= 1
UNET SFX= 1
UNET 1D Methodology=Finite Difference
UNET DSS MLevel= 1
UNET Pardiso=0
UNET DZMax Abort= 0
UNET Use Existing IB Tables= 0
UNET Froude Reduction=False
UNET Froude Limit= 0
UNET Froude Power= 0
UNET D1 Cores= 0
UNET D2 Coriolis=0
UNET D2 Cores= 0
UNET D2 Theta= 1
UNET D2 Theta Warmup= 1
UNET D2 Z Tol= 0.01
UNET D2 Volume Tol= 0.01
UNET D2 Max Iterations= 20
UNET D2 Equation= 0
UNET D2 RampUpFraction=0.1
UNET D2 TimeSlices= 1
UNET D2 BCVolumeCheck=0
UNET D1D2 MaxIter= 0
UNET D1D2 ZTol=0.01
UNET D1D2 QTol=0.1
UNET D1D2 MinQTol=1
Write IC File= 0
Write IC File at Fixed DateTime=0
Write IC File at Sim End=0
Echo Input=False
Echo Parameters=False
Echo Output=False
Write Detailed= 0
HDF Write Warmup=0
HDF Write Time Slices=0
HDF Flush=0
HDF Face Node Velocities=0
HDF Compression= 1
HDF Chunk Size= 1
HDF Spatial Parts= 1
HDF Use Max Rows=0
HDF Fixed Rows= 1
Calibration Method= 0
Calibration Iterations= 20
Calibration Max Change=0.05
Calibration Tolerance=0.2
Calibration Maximum=1.5
Calibration Minimum=0.5
Calibration Optimization Method= 1
WQ AD Non Conservative
WQ ULTIMATE=-1
WQ Max Comp Step=1HOUR
WQ Output Interval=15MIN
WQ Output Selected Increments= 0
WQ Output face flow=0
WQ Output face velocity=0
WQ Output face area=0
WQ Output face dispersion=0
WQ Output cell volume=0
WQ Output cell surface area=0
WQ Output cell continuity=0
WQ Output cumulative cell continuity=0
WQ Output face conc=0
WQ Output face dconc_dx=0
WQ Output face courant=0
WQ Output face peclet=0
WQ Output face adv mass=0
WQ Output face disp mass=0
WQ Output cell mass=0
WQ Output cell source sink temp=0
WQ Output nsm pathways=0
WQ Output nsm derived pathways=0
WQ Output MaxMinRange=-1
WQ Daily Max Min Mean=-1
WQ Daily Range=0
WQ Daily Time=0
WQ Create Restart=0
WQ Fixed Restart=0
WQ System Summary=0
WQ Write To DSS=0
WQ Use Fixed Temperature=0
Sorting and Armoring Iterations= 10
XS Update Threshold= 0.02
Bed Roughness Predictor= 0
Hydraulics Update Threshold= 0.02
Energy Slope Method= 1
Volume Change Method= 1
Sediment Retention Method= 0
XS Weighting Method= 0
Number of US Weighted Cross Sections= 1
Number of DS Weighted Cross Sections= 1
Upstream XS Weight=0
Main XS Weight=1
Downstream XS Weight=0
Number of DS XS's Weighted with US Boundary= 1
Upstream Boundary Weight= 1
Weight of XSs Associated with US Boundary= 0
Number of US XS's Weighted with DS Boundary= 1
Downstream Boundary Weight= 0.5
Weight of XSs Associated with DS Boundary= 0.5
Percentile Method= 0
Sediment Output Level= 3
Mass or Volume Output= 0
Output Increment Type= 1
Profile and TS Output Increment= 1
XS Output Flag= 0
XS Output Increment= 10
Write Gradation File= 0
Read Gradation Hotstart= 0
Write HDF5 File= 1
Write Binary Output= 1
Write DSS Sediment File= 0
SV Curve= 0
Specific Gage Flag= 0

--- MILLCK.f01 (steady flow) ---

Flow Title=Flows
Program Version=5.07
Number of Profiles= 7
Profile Names=01pct,FW,10pct,04pct,02pct,0_2pct,01plus
River Rch & RM=MILLCK,Main            ,18120
     430     430     225     301     363     604     636
River Rch & RM=MILLCK,Main            ,17770
     720     720     384     509     611    1002    1065
River Rch & RM=MILLCK,Main            ,14043
     802     802     429     567     681    1113    1186
River Rch & RM=MILLCK,Main            ,10957
    1500    1500     823    1075    1281    2058    2219
River Rch & RM=MILLCK,Main            ,10039
    1669    1669     920    1199    1427    2286    2469
River Rch & RM=MILLCK,Main            ,4951
    1865    1865    1031    1342    1595    2548    2758
River Rch & RM=MILLCK,Main            ,0
    4843    4843    2780    3552    4178    6500    7164
Boundary for River Rch & Prof#=MILLCK,Main            , 1
Up Type= 0
Dn Type= 3
Dn Slope=0.01062
Boundary for River Rch & Prof#=MILLCK,Main            , 2
Up Type= 0
Dn Type= 3
Dn Slope=0.01062
Boundary for River Rch & Prof#=MILLCK,Main            , 3
Up Type= 0
Dn Type= 3
Dn Slope=0.01062
Boundary for River Rch & Prof#=MILLCK,Main            , 4
Up Type= 0
Dn Type= 3
Dn Slope=0.01062
Boundary for River Rch & Prof#=MILLCK,Main            , 5
Up Type= 0
Dn Type= 3
Dn Slope=0.01062
Boundary for River Rch & Prof#=MILLCK,Main            , 6
Up Type= 0
Dn Type= 3
Dn Slope=0.01062
Boundary for River Rch & Prof#=MILLCK,Main            , 7
Up Type= 0
Dn Type= 3
Dn Slope=0.01062
DSS Import GetInterval= 0
DSS Import GetPeak= 0
DSS Import FillOption= 0

--- MILLCK.g01 (geometry) ---

Geom Title=Geometry
Program Version=5.07

River Reach=MILLCK          ,Main
Reach XY= 30
2022608.60400003307173.5520000162022377.00700003306682.580000013
2022262.42399999 306156.88500002     2022752.007305797.510000005
2023124.57600002305355.8439999972023662.42400001      305128.066
     2024094.021304755.8439999972024484.21200003304212.007000014
      2025145.67303021.4679999952025391.10699999 301575.74000001
2025077.35800004301211.507000014      2024645.67301134.316000015
2024094.45500004 300484.142000022023504.69100003300153.908000022
     2022694.715299373.4650000182022690.37500004299055.756999999
2022573.18800002       298947.25     2022617.892298783.621000022
2022494.62800002298697.684000015     2022403.917298129.541999996
2022215.91900001297852.319000021     2022244.889297530.931000009
2022093.84700003297146.5550000072022035.77400002      296310.213
2021918.12456293296189.1964439992021950.70500001295665.248000011
2021799.66299999295374.4490000012021616.61900003294264.322000012
2021089.55800003293438.2660000032020526.82572167293072.471231803

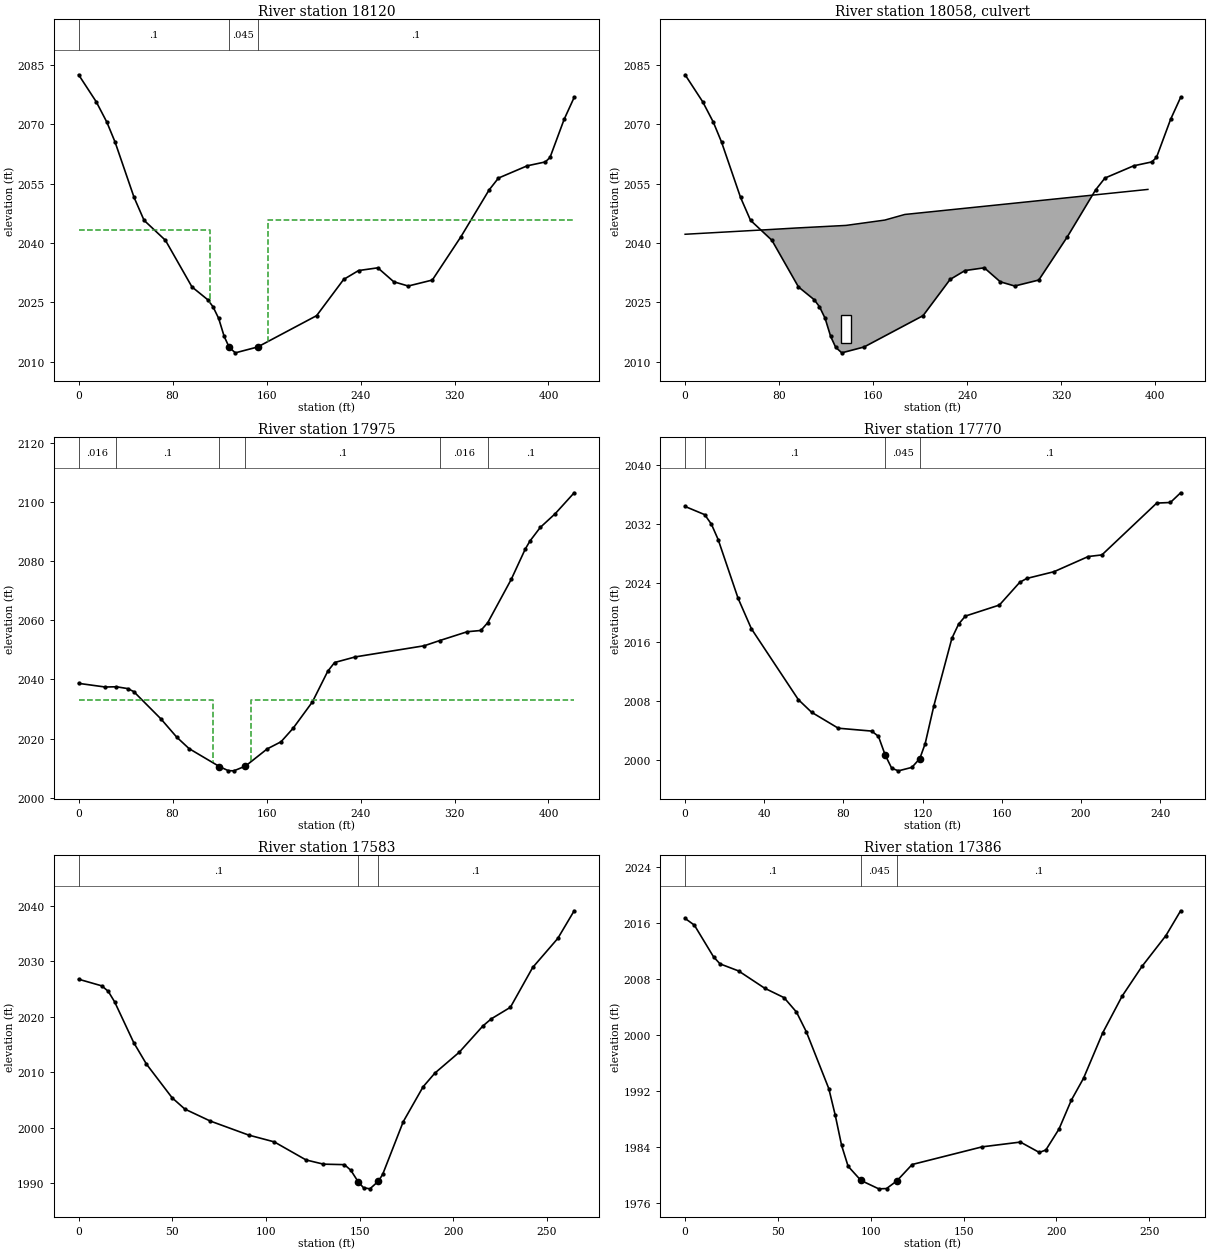
Type RM Length L Ch R = 1 ,18120   ,146.5,144.7,148.9
XS GIS Cut Line= 4
2022700.42645089307068.8337884752022590.29767623307184.469001866
2022463.64958538307279.4550700092022378.29978502307338.649286387
#Sta/Elev= 30
       0 2082.51      15 2075.68      24 2070.55      31 2065.52    47.2 2051.51
    55.7 2045.72    73.9 2040.67    96.5 2028.88   109.9 2025.65   114.4 2023.87
   119.2 2020.94   123.9 2016.38   128.2 2013.61   133.4 2012.22   152.4  2013.7
   202.6 2021.62   225.6 2030.77   238.3 2033.02   254.7 2033.71   268.3 2030.18
   280.6 2029.11   301.1 2030.62   325.5 2041.59   349.4 2053.38   357.4  2056.4
   381.9  2059.5   397.3 2060.48   401.3 2061.61   413.3 2071.23421.8647  2076.8
#Mann= 3 ,-1 , 0
       0      .1       0   128.2    .045       0   152.4      .1       0
#XS Ineff= 2 , 0
             112 2043.39     161         2045.78
Permanent Ineff=
       F       F
Bank Sta=128.2,152.4
XS Rating Curve= 0 ,0
Exp/Cntr(USF)=0,0
Exp/Cntr=0.5,0.3

Type RM Length L Ch R = 2 ,18058   ,,,
BEGIN DESCRIPTION:
County Route 20
Survey ID: MIC050
END DESCRIPTION:
Bridge Culvert--1,0,-1,-1, 0
Deck Dist Width WeirC Skew NumUp NumDn MinLoCord MaxHiCord MaxSubmerge Is_Ogee
58,45,2.6,0, 7, 7, , , 0.98, 0, 0,0,,
       0      72      95     137     170     187     394
2042.1942043.3872043.7862044.4352045.7812047.199 2053.53
                                                        
       0      72      95     137     170     187     394
2042.1942043.3872043.7862044.4352045.7812047.199 2053.53
                                                        
BR Coef=-1 , 1 , 0 ,, 0 ,,,0.8,0,1.2,0,
WSPro=,,,, 1 ,,,, 0 ,,,, 0 ,,,,-1 ,-1 ,-1 , 0 , 0 , 0 , 0 , 0
Culvert=2,7,9,120,0.012,0.4,1,8,1,2014.716,137,2008.368,130,Culvert #1  , 0 ,13
     137     130
BC Culvert Barrel=1,Barrel1,0
Culvert Bottom n=0.012
BC Design=,, 0 ,, 0 ,,,,,,
BC Use User HTab Curves=0
BC User HTab FreeFlow(D)= 0

Type RM Length L Ch R = 1 ,17975   ,178.2,205.6,209
XS GIS Cut Line= 4
2022624.04878619306947.0245818362022513.92001153307062.659795227
2022387.27192067307157.6458633692022301.92212031307216.840079748
#Sta/Elev= 30
       0 2038.69    22.6 2037.46    32.2 2037.54    41.7 2036.93    46.9 2035.92
    70.1 2026.68    83.5 2020.54      94 2016.67   119.8 2010.62   127.3 2009.23
   132.1 2009.16     142 2010.76   160.5 2016.56   172.3 2018.97   182.6 2023.54
     199 2032.42   212.1 2042.79   217.9 2045.73   235.6 2047.63   294.2 2051.38
   307.4 2053.14   330.9 2056.13   342.4 2056.54   348.3 2059.19   368.3 2073.81
   380.2 2084.01   384.2 2086.73     393 2091.33   405.7 2095.96421.8647 2103.03
#Mann= 6 ,-1 , 0
       0    .016       0    32.2      .1       0   119.8    .045       0
     142      .1       0   307.4    .016       0   348.3      .1       0
#XS Ineff= 2 , 0
             114    2033     147            2033
Permanent Ineff=
       F       F
Bank Sta=119.8,142
XS Rating Curve= 0 ,0
Exp/Cntr(USF)=0,0
Exp/Cntr=0.5,0.3

Type RM Length L Ch R = 1 ,17770   ,187.7,186.5,182.8
XS GIS Cut Line= 3
2022598.36770529306834.4784166142022456.57690792306868.893658694
2022357.46101073306901.932291092
#Sta/Elev= 30
       0 2034.39     9.9 2033.28    13.3 2031.98    16.7  2029.9    26.8  2021.9
    33.5 2017.78    57.2 2008.16    63.9 2006.44    77.4 2004.27    94.3 2003.88
    97.7 2003.16   101.1 2000.63   104.4 1998.83   107.8 1998.48   114.6 1998.95
   118.6 2000.15   121.3 2002.17   125.7 2007.32   134.8 2016.48   138.2 2018.41
   141.6  2019.5   158.8    2021   169.1 2024.09   172.6 2024.61   186.4 2025.53
   203.7 2027.59   210.6 2027.81   238.3 2034.85   245.2 2034.93 250.385 2036.25
#Mann= 4 ,-1 , 0
       0    .016       0     9.9      .1       0   101.1    .045       0
   118.6      .1       0
Bank Sta=101.1,118.6
XS Rating Curve= 0 ,0
Exp/Cntr(USF)=0,0
Exp/Cntr=0.3,0.1

Type RM Length L Ch R = 1 ,17583   ,197.9,197.3,194.8
XS GIS Cut Line= 2
2022535.04365986306667.9086449432022280.37086847306739.492348471
#Sta/Elev= 30
       0 2026.75    12.4 2025.55    15.8 2024.57    19.2 2022.68    29.4 2015.33
    36.2 2011.45    49.9 2005.38    56.7 2003.34    70.3 2001.18    90.8 1998.65
   104.4 1997.43   121.4 1994.17   130.7 1993.41   141.9 1993.32   145.3 1992.31
   149.3  1990.2   152.1 1989.16   155.5 1988.96     160 1990.33   162.3 1991.56
   173.3 2001.07   183.9 2007.36   190.2 2009.83   203.2 2013.59   215.8 2018.32
   220.3 2019.61   230.5 2021.69   242.4 2028.87   255.8 2034.11 264.542 2039.09
#Mann= 3 , 0 , 0
       0      .1       0   149.3    .045       0     160      .1       0
Bank Sta=149.3,160
XS Rating Curve= 0 ,0
Exp/Cntr(USF)=0,0
Exp/Cntr=0.3,0.1

Type RM Length L Ch R = 1 ,17386   ,127.8,126.4,124.2
XS GIS Cut Line= 3
2022521.27756303306490.3259958072022402.88913027306528.871066938
2022266.60477163306570.169357434
#Sta/Elev= 30
       0 2016.63       5 2015.67    15.3 2011.16    18.8 2010.15    28.8 2009.14
    42.9 2006.67    53.3 2005.33      60 2003.27    65.3 2000.46    77.4 1992.36
    80.9 1988.53    84.3 1984.25    87.8 1981.28    94.7 1979.26   104.3 1978.06
   108.5  1978.1  114.03 1979.19   122.3 1981.53     160 1984.05   180.6 1984.73
   190.8 1983.25   194.3  1983.6   201.4 1986.59     208 1990.69   214.6 1993.83
     225 2000.34   235.4 2005.55   246.1 2009.79     259 2014.19266.9095 2017.72
#Mann= 3 , 0 , 0
       0      .1       0    94.7    .045       0  114.03      .1       0
Bank Sta=94.7,114.03
XS Rating Curve= 0 ,0
Exp/Cntr(USF)=0,0
Exp/Cntr=0.3,0.1

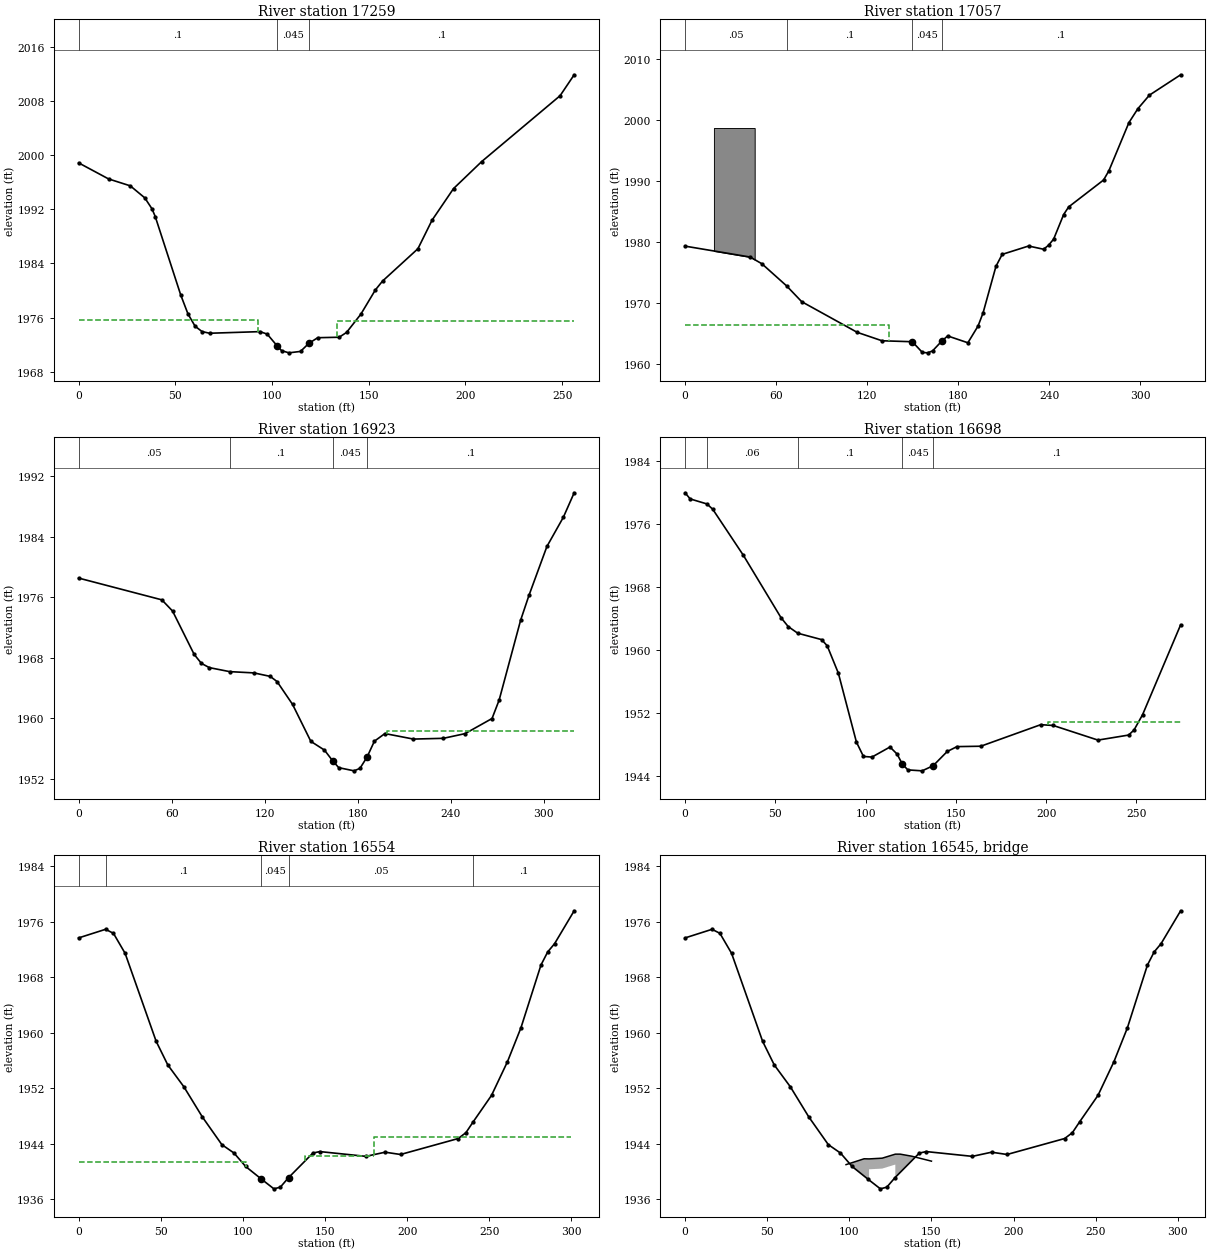
Type RM Length L Ch R = 1 ,17259   ,188.4,202.4,201.9
XS GIS Cut Line= 3
 2022474.4728338306354.0416371682022328.55220738306432.508389112
2022247.33223607306472.430069925
#Sta/Elev= 30
       0 1998.89    15.5 1996.51    26.7 1995.49    34.2 1993.71    37.9  1992.1
    39.6 1990.95    52.8 1979.32    56.5 1976.55    60.2 1974.71    63.8 1973.92
    67.7 1973.67    93.8 1973.91    97.5 1973.54   102.6 1971.81   104.9  1971.1
   108.7 1970.77   114.7 1970.98     119 1972.17   123.6 1973.01   134.7 1973.08
   138.5 1973.79   145.9 1976.49   153.4 1980.08   157.1 1981.39   175.4 1986.18
   182.7  1990.4   193.8 1995.08   208.4 1999.09   248.9 2008.83 256.181 2011.93
#Mann= 3 ,-1 , 0
       0      .1       0   102.6    .045       0     119      .1       0
#XS Ineff= 2 , 0
           92.79 1975.59  133.35         1975.53
Permanent Ineff=
       F       F
Bank Sta=102.6,119
XS Rating Curve= 0 ,0
Exp/Cntr(USF)=0,0
Exp/Cntr=0.3,0.1

Type RM Length L Ch R = 1 ,17057   ,118.3,133.5,152.7
XS GIS Cut Line= 4
2022412.52539806306264.5620077582022299.64340403306253.549130292
2022189.51462937306272.821665858 2022089.0221225306285.211153007
#Sta/Elev= 30
       0 1979.33    42.9 1977.54    50.6 1976.44    66.9 1972.81    76.8 1970.23
   113.4  1965.2   129.7 1963.82   149.7 1963.66   156.3 1961.91   159.7 1961.84
     163 1962.15   169.2 1963.79     173 1964.61   186.3 1963.49     193 1966.23
   196.3 1968.38   204.8 1976.02   208.9 1977.98   226.3 1979.35   236.2 1978.82
   239.5 1979.49   242.8 1980.48   249.4 1984.51   252.7 1985.76   275.7 1990.17
   279.2 1991.68   292.4 1999.58   298.3 2001.86   305.9 2004.08326.4737 2007.42
#Mann= 4 ,-1 , 0
       0     .05       0    66.9      .1       0   149.7    .045       0
   169.2      .1       0
#XS Ineff= 2 , 0
          134.08 1966.47
Permanent Ineff=
       F       F
#Block Obstruct= 1 ,-1
   18.99   45.85 1998.69
Bank Sta=149.7,169.2
XS Rating Curve= 0 ,0
Exp/Cntr(USF)=0,0
Exp/Cntr=0.3,0.1

Type RM Length L Ch R = 1 ,16923   ,224.3,225.5,225.5
XS GIS Cut Line= 3
2022412.52539806306252.1725206092022263.85155227306121.394600703
2022178.50175191 306034.66819066
#Sta/Elev= 30
       0 1978.53    53.7 1975.65    60.6 1974.17    74.5 1968.45    79.2 1967.25
    84.3 1966.69    97.4 1966.16   113.1 1965.99   123.6 1965.53     128 1964.85
     138 1961.83   149.8 1956.94   158.6 1955.78   163.8 1954.39   167.8 1953.46
   177.7 1953.04   181.5 1953.37   186.1 1954.87   190.8 1956.96   197.6 1957.97
     216 1957.24   235.3 1957.34   249.3 1957.96   266.7 1959.96   271.3 1962.41
   285.1 1972.93   290.5 1976.23   302.1 1982.71   312.7 1986.57319.6872 1989.81
#Mann= 4 ,-1 , 0
       0     .05       0    97.4      .1       0   163.8    .045       0
   186.1      .1       0
#XS Ineff= 2 , 0
                          198.76         1958.29
Permanent Ineff=
       F       F
#Block Obstruct= 2 , 0
            51.3 1998.53
Bank Sta=163.8,186.1
XS Rating Curve= 0 ,0
Exp/Cntr(USF)=0,0
Exp/Cntr=0.3,0.1

Type RM Length L Ch R = 1 ,16698   ,147,144.2,139.4
XS GIS Cut Line= 2
2022561.19924384306106.2518941872022367.09727851305912.149928853
#Sta/Elev= 30
       0 1979.98     2.8  1979.2    12.1 1978.56    15.3 1977.89    32.3 1972.02
    53.1 1964.11    57.1 1962.97    62.4 1962.12    75.6 1961.31    78.7 1960.53
    84.9 1957.04    94.9 1948.28    98.8 1946.45   103.5 1946.37   113.5 1947.65
   117.4 1946.76   120.4 1945.46   123.4 1944.74   131.3 1944.62   137.4 1945.27
   145.2 1947.08   150.6  1947.7   163.8 1947.75     197 1950.49   203.9 1950.39
   228.7 1948.53   245.7 1949.17   248.7 1949.82   253.4 1951.75274.5016 1963.19
#Mann= 5 ,-1 , 0
       0    .016       0    12.1     .06       0    62.4      .1       0
   120.4    .045       0   137.4      .1       0
#XS Ineff= 2 , 0
                          200.79          1950.8
Permanent Ineff=
       F       F
Bank Sta=120.4,137.4
XS Rating Curve= 0 ,0
Exp/Cntr(USF)=0,0
Exp/Cntr=0.5,0.3

Type RM Length L Ch R = 1 ,16554   ,31.8,31.3,31.5
XS GIS Cut Line= 4
2022684.91723843305995.7838683382022599.98000785305939.817476099
2022571.00916952305921.3814880672022438.00668443305822.617266467
#Sta/Elev= 30
       0 1973.67    16.4 1974.91    21.2 1974.33    28.3 1971.45    47.2 1958.77
    54.3 1955.36    64.1 1952.21    75.3 1947.88    87.2 1943.88    94.6 1942.67
   101.7 1940.73   111.2 1938.93   118.9 1937.51   122.8 1937.75   127.8 1939.12
   142.6 1942.66   146.8 1942.88   174.9 1942.19   186.6 1942.79     196 1942.46
   231.1 1944.76   235.8  1945.6   240.3 1947.19   251.4 1950.98   261.1 1955.83
   269.3 1960.71   281.5 1969.76   285.6 1971.65   289.8 1972.84301.7199 1977.58
#Mann= 5 ,-1 , 0
       0    .016       0    16.4      .1       0   111.2    .045       0
   127.8     .05       0   240.3      .1       0
#XS Ineff= 3 ,-1
       0     102 1941.31     138     180 1942.21     180     300    1945
Permanent Ineff=
       F       F       F
Bank Sta=111.2,127.8
XS Rating Curve= 0 ,0
Exp/Cntr(USF)=0,0
Exp/Cntr=0.5,0.3

Type RM Length L Ch R = 3 ,16545   ,,,
BEGIN DESCRIPTION:
Private Driveway
Survey ID: MIC040
END DESCRIPTION:
Bridge Culvert--1,0,-1,-1, 0
Deck Dist Width WeirC Skew NumUp NumDn MinLoCord MaxHiCord MaxSubmerge Is_Ogee
10,12,2.6,0, 10, 9, , , 0.98, 0, 0,0,,
      98     109     112     112     120     128     128     131     138     150
    19411941.8411941.8251941.8251941.9291942.5091942.5091942.5091942.213  1941.5
                        1940.3251940.4291941.009
      98     109     115     115     120     131     131     138     150
    19411941.8411941.8251941.8251941.9291942.5091942.5091942.213  1941.5
                        1940.3251940.4291941.009
BR Coef=-1 , 1 , 0 ,, 0 ,,,0.8,0,1.2,0,
WSPro=,,,, 1 ,,,, 0 ,,,, 0 ,,,,-1 ,-1 ,-1 , 0 , 0 , 0 , 0 , 0
BR U #Sta/Elev= 30
       0 1973.67    16.4 1974.91    21.2 1974.33    28.3 1971.45    47.2 1958.77
    54.3 1955.36    64.1 1952.21    75.3 1947.88    87.2 1943.88    94.6 1942.67
   101.7 1940.73   111.2 1938.93   118.9 1937.51   122.8 1937.75   127.8 1939.12
   142.6 1942.66   146.8 1942.88   174.9 1942.19   186.6 1942.79     196 1942.46
   231.1 1944.76   235.8  1945.6   240.3 1947.19   251.4 1950.98   261.1 1955.83
   269.3 1960.71   281.5 1969.76   285.6 1971.65   289.8 1972.84  301.72 1977.58
BR U #Mann= 5
       0    .016    16.4      .1   111.2     .04   127.8     .05   240.3      .1
BR D #Sta/Elev= 188
       0 1971.83     5.2 1972.11     8.4 1972.25    10.7  1972.3    13.1 1972.28
    15.5 1971.89      17 1971.46    17.9 1971.16    19.1 1970.62      21  1969.7
      25 1967.57    28.8 1965.57      31  1964.3    32.7 1963.28    36.7 1960.75
    39.2 1959.08    44.5  1955.3    48.9 1952.29    52.4 1949.85    54.9 1948.03
    56.3 1946.92    58.1 1945.66    60.2 1944.31    60.5 1944.18    60.8 1944.02
    62.9 1943.39    64.2 1943.09    65.2 1942.91    66.8 1942.72      70 1942.49
      72 1942.33    78.7 1942.01    79.4 1941.95    79.9 1941.91    82.1 1941.71
    83.8 1941.57    91.7    1941    96.6 1940.76   105.5 1940.37   107.3 1940.28
   107.9 1940.24   108.7 1940.14   110.3 1939.91   111.2 1939.68   112.6 1939.16
   114.8 1938.11     115 1938.03   115.1 1937.98   115.6 1937.78   117.4 1937.06
     119 1936.56   119.8 1936.49   120.9 1936.31   122.1 1936.26   122.9 1936.24
   124.5 1936.32   126.8 1936.47   126.9 1936.49     127 1936.53   129.3 1937.18
   130.7 1937.66   131.6 1938.15   133.2 1938.93     134 1939.43   134.6 1939.69
   136.1 1940.19   136.4  1940.3   137.5 1940.54   138.7 1940.81     139 1940.82
   144.5  1940.8   145.8 1940.82   146.7 1940.84   150.5  1940.8   150.8  1940.8
   152.8 1940.87   153.3  1940.9   154.9 1940.97   155.1 1940.98   155.5    1941
   157.5 1941.14     159 1941.23   162.2 1941.33   163.1 1941.36   164.5 1941.43
   166.5 1941.54   166.9 1941.57   167.2 1941.59   169.2 1941.71   171.3 1941.84
   171.6 1941.86     172 1941.88   173.9 1941.96   180.9 1942.17     183 1942.25
   187.6 1942.55     188 1942.57   188.5 1942.59   190.3 1942.75   191.7 1942.89
   192.7 1942.96     194 1943.06     195 1943.17   195.8 1943.26   197.4 1943.42
   199.5 1943.63   199.7 1943.66   199.9 1943.68     201 1943.83     202 1943.97
     204 1944.21   204.4 1944.27     205 1944.35   206.7 1944.63     208 1944.83
   209.1 1944.98   210.5 1945.17   211.4  1945.3   212.1 1945.39     216 1945.85
   216.1 1945.87   216.2 1945.88   218.5 1946.09   220.3 1946.24   220.8 1946.28
   224.4 1946.52   225.5 1946.65     227 1946.81   227.8 1946.93   228.5 1947.06
   230.2 1947.54   232.5 1948.31   232.5 1948.32   232.7 1948.41   234.9 1949.46
   236.6 1950.42   237.2 1950.76     238 1951.27   239.6 1952.28   240.7  1953.1
   241.9 1953.95   244.8 1956.07   246.6 1957.35   248.6 1958.74   248.9 1958.96
     249 1958.99     249 1959.02   251.3 1960.27   254.5 1962.12   258.3 1964.25
     260 1965.23   260.7 1965.62   261.2 1965.91     263 1967.02   264.5  1967.9
   265.3 1968.38   265.4 1968.45   265.5 1968.56   267.7  1970.1   269.3  1971.3
   270.1 1971.79     271 1972.43   272.4 1973.23   273.4 1973.77   274.7 1974.28
   276.5 1974.83   277.1 1975.01   277.5 1975.13   279.4 1975.79   280.3 1976.12
   281.6 1976.58   281.8 1976.66     282 1976.77   284.1 1977.74   285.7 1978.41
   286.5 1978.72   287.5 1979.12   289.8 1980.01   291.2 1980.56     293 1981.31
   293.9 1981.65   295.9  1982.4   296.2 1982.52   297.9 1983.12   298.2 1983.21
   298.5 1983.32   300.5 1983.95  301.72 1984.29
BR D #Mann= 5
       0    .016    13.1      .1   114.8     .04   131.6     .05   240.7      .1
BC Design=,, 0 ,, 0 ,,,,,,
BC Use User HTab Curves=0
BC User HTab FreeFlow(D)= 0

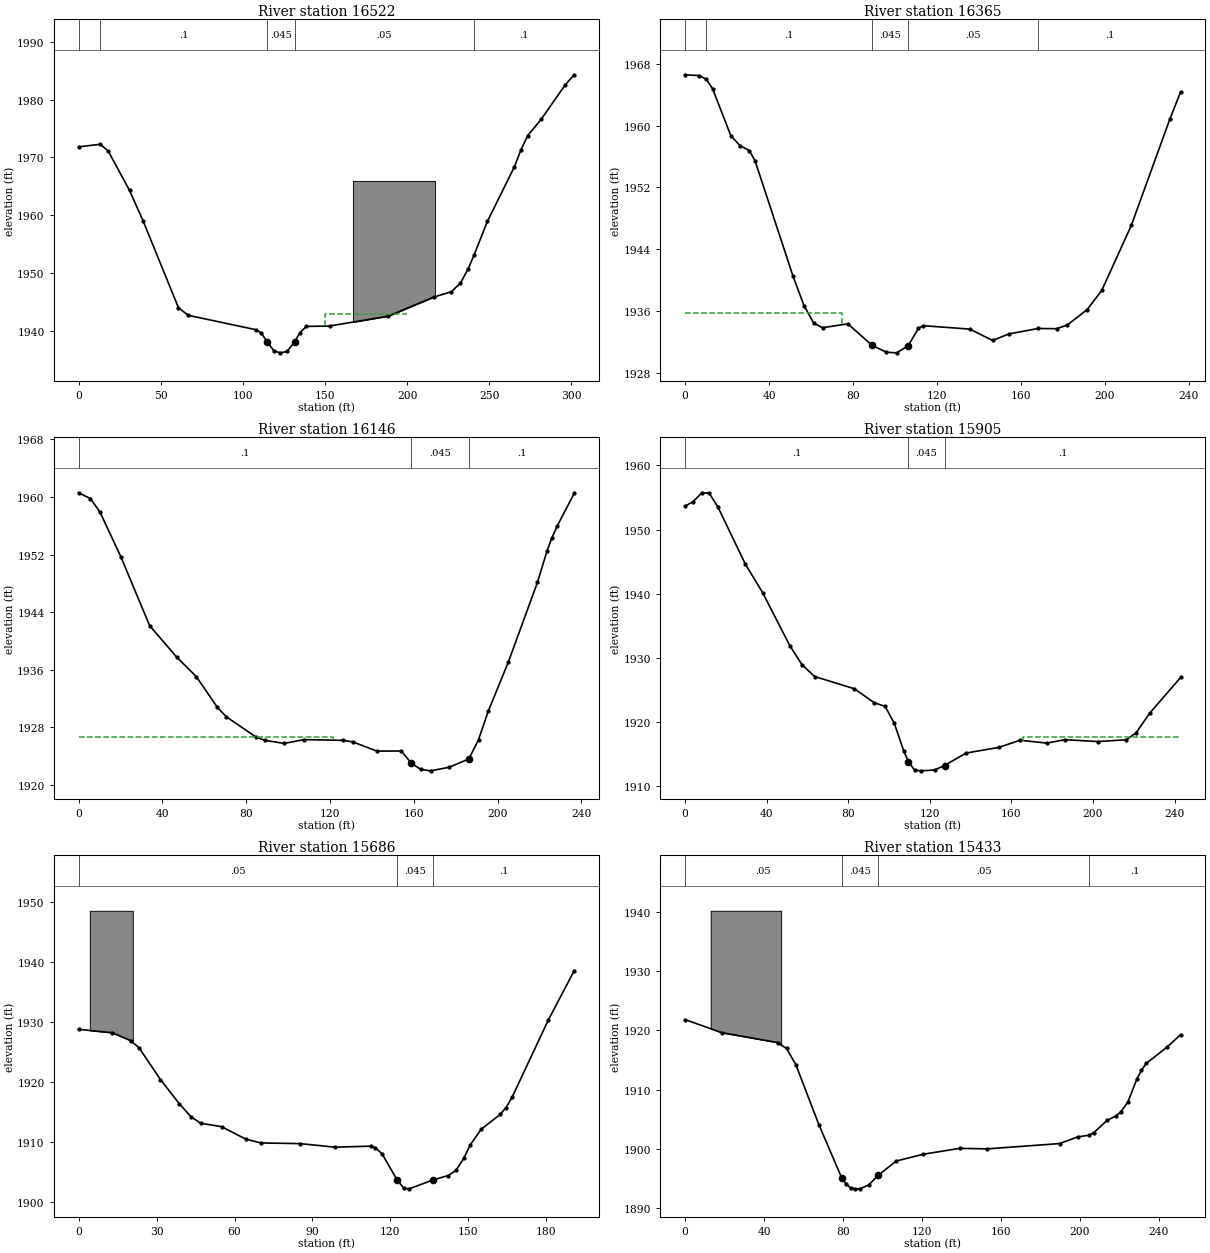
Type RM Length L Ch R = 1 ,16522   ,151.3,157.7,162.6
XS GIS Cut Line= 4
2022704.67008275 305971.422027012022619.73285217305915.455634771
2022590.76201384305897.0196467392022457.75952875305798.255425139
#Sta/Elev= 30
       0 1971.83    13.1 1972.28    17.9 1971.16      31  1964.3    39.2 1959.08
    60.8 1944.02    66.8 1942.72   107.9 1940.24   111.2 1939.68   114.8 1938.11
     119 1936.56   122.9 1936.24   126.9 1936.49   131.6 1938.15   134.6 1939.69
   138.7 1940.81   152.8 1940.87   188.5 1942.59   216.1 1945.87     227 1946.81
   232.5 1948.31   237.2 1950.76   240.7  1953.1   248.9 1958.96   265.3 1968.38
   269.3  1971.3   273.4 1973.77   281.6 1976.58   296.2 1982.52301.7199 1984.29
#Mann= 5 ,-1 , 0
       0    .016       0    13.1      .1       0   114.8    .045       0
   131.6     .05       0   240.7      .1       0
#XS Ineff= 3 ,-1
       0111.6667    1939134.3333     150    1939     150     200    1943
Permanent Ineff=
       F       F       F
#Block Obstruct= 1 ,-1
  167.02  216.93 1965.95
Bank Sta=114.8,131.6
XS Rating Curve= 0 ,0
Exp/Cntr(USF)=0,0
Exp/Cntr=0.5,0.3

Type RM Length L Ch R = 1 ,16365   ,215.8,218.8,199.3
XS GIS Cut Line= 3
2022796.59949968305888.7475642382022718.13274773305799.267934828
2022642.41921515305709.788305418
#Sta/Elev= 30
       0 1966.56     6.7 1966.46    10.1 1965.97    13.1 1964.76    21.8 1958.69
    26.2 1957.39    30.6 1956.77    33.4  1955.4    51.5 1940.48    56.7 1936.71
    61.3 1934.45    65.5 1933.86    77.6 1934.36    89.2 1931.56      96 1930.69
   100.8 1930.61   106.3 1931.51   111.2 1933.76   113.5 1934.12   135.7 1933.68
   146.6 1932.21   154.3 1933.05   168.3 1933.76   177.1 1933.73   182.2 1934.21
   191.6 1936.18   198.6 1938.67   212.7 1947.08   231.1 1960.84236.2252 1964.35
#Mann= 5 ,-1 , 0
       0    .016       0    10.1      .1       0    89.2    .045       0
   106.3     .05       0   168.3      .1       0
#XS Ineff= 2 , 0
           74.79 1935.78
Permanent Ineff=
       F       F
Bank Sta=89.2,106.3
XS Rating Curve= 0 ,0
Exp/Cntr(USF)=0,0
Exp/Cntr=0.3,0.1

Type RM Length L Ch R = 1 ,16146   ,234.8,240.9,243.8
XS GIS Cut Line= 3
 2022950.7797842305751.0865959152022814.49542556305616.178846959
2022782.83340284305584.516824245
#Sta/Elev= 30
       0 1960.59     5.6 1959.79    10.2  1957.9    20.1 1951.73    33.9 1942.12
    46.8 1937.75    56.2 1935.03    66.2 1930.77    70.5 1929.46    84.7 1926.63
    88.8 1926.19    98.1 1925.75   107.5 1926.28   126.2 1926.18   130.8 1925.97
   142.4 1924.68     154  1924.7   158.7 1923.04   163.3 1922.13   168.1 1921.94
     177 1922.45   186.3  1923.6   190.9 1926.29   195.5 1930.21   205.1 1937.05
     219 1948.13   223.6 1952.52   225.9 1954.32   228.5 1956.02236.5411 1960.49
#Mann= 3 ,-1 , 0
       0      .1       0   158.7    .045       0   186.3      .1       0
#XS Ineff= 2 , 0
          121.27  1926.6
Permanent Ineff=
       F       F
Bank Sta=158.7,186.3
XS Rating Curve= 0 ,0
Exp/Cntr(USF)=0,0
Exp/Cntr=0.3,0.1

Type RM Length L Ch R = 1 ,15905   ,216.3,218.6,210.3
XS GIS Cut Line= 3
2023117.34955587305616.1788469592023065.03838791305552.854801531
2022957.66283261 305433.08975909
#Sta/Elev= 30
       0 1953.65     3.9 1954.34     8.2 1955.73    11.8 1955.67    16.1 1953.51
    29.5 1944.65      38 1940.19    51.4 1931.89    57.3 1928.97    63.5 1927.12
      83 1925.21    92.8 1923.03    98.1 1922.46   102.6 1919.82   107.2 1915.54
   109.5 1913.87   112.5 1912.55   115.7 1912.43   122.3 1912.56   127.2 1913.26
   137.8  1915.2   153.7 1916.07   164.2 1917.19   177.4 1916.75   186.2 1917.28
   202.5 1916.99   216.4 1917.27   221.1 1918.34     228 1921.48242.9878 1926.97
#Mann= 3 ,-1 , 0
       0      .1       0   109.5    .045       0   127.2      .1       0
#XS Ineff= 2 , 0
                          165.77         1917.66
Permanent Ineff=
       F       F
Bank Sta=109.5,127.2
XS Rating Curve= 0 ,0
Exp/Cntr(USF)=0,0
Exp/Cntr=0.3,0.1

Type RM Length L Ch R = 1 ,15686   ,253.4,253.5,250.3
XS GIS Cut Line= 2
2023228.85494021305444.1026365562023107.71328809305296.805400451
#Sta/Elev= 30
       0 1928.74      13 1928.18      20 1926.87    23.3 1925.64    31.5 1920.36
    38.7 1916.36    43.3 1914.14      47 1913.08      55 1912.51    64.3 1910.44
      70  1909.8    85.3 1909.68    98.7 1909.09   112.5 1909.26   114.2 1908.97
   116.7 1908.03   122.6  1903.6   125.2 1902.23   127.2 1902.14   136.5 1903.64
   142.2 1904.35   145.2 1905.21   148.2 1907.21   150.7 1909.45   154.9 1912.07
   162.2 1914.54   164.5  1915.7   166.9 1917.49   180.8 1930.33190.7139 1938.52
#Mann= 3 ,-1 , 0
       0     .05       0   122.6    .045       0   136.5      .1       0
#Block Obstruct= 1 ,-1
     4.3   20.85 1948.52
Bank Sta=122.6,136.5
XS Rating Curve= 0 ,0
Exp/Cntr(USF)=0,0
Exp/Cntr=0.3,0.1

Type RM Length L Ch R = 1 ,15433   ,94.6,97,98.4
Node Name=E
XS GIS Cut Line= 2
2023444.98266048305328.4674231652023268.77662102305149.508164346
#Sta/Elev= 30
       0 1921.81    18.6 1919.61    46.9 1917.94    51.4 1916.94    56.2 1914.16
    67.8 1904.09    79.3 1895.17    81.7 1894.08    83.9 1893.39    86.3 1893.27
    88.7 1893.28    93.1 1893.94    97.9 1895.55     107 1897.96   120.8 1899.11
   139.2  1900.1     153 1900.01   189.8  1900.9     199 1902.03   204.7 1902.31
     207  1902.7   213.9 1904.82   218.6 1905.61   220.9 1906.29   224.4 1907.89
     229 1911.83   231.3 1913.26   233.7 1914.42   244.1 1917.13251.1473 1919.27
#Mann= 4 ,-1 , 0
       0     .05       0    79.3    .045       0    97.9     .05       0
   204.7      .1       0
#Block Obstruct= 1 ,-1
   12.98   48.67 1940.16
Bank Sta=79.3,97.9
XS Rating Curve= 0 ,0
Exp/Cntr(USF)=0,0
Exp/Cntr=0.5,0.3