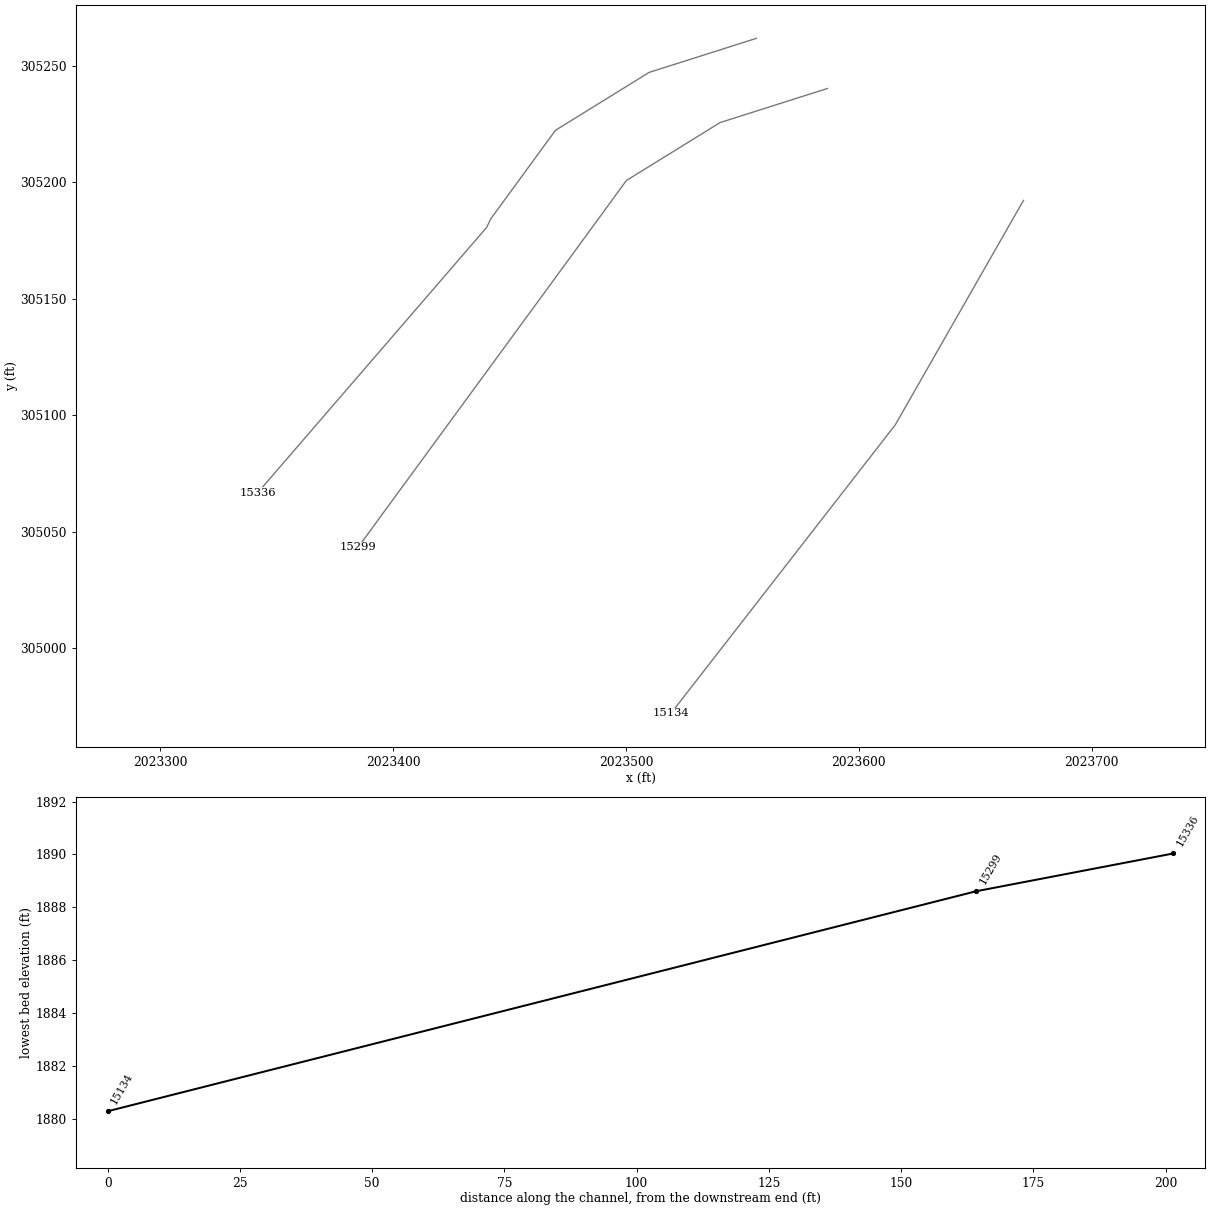
HEC-RAS study MILLCK.prj: MILLCK

--- MILLCK.g01 (geometry) --- (continued)

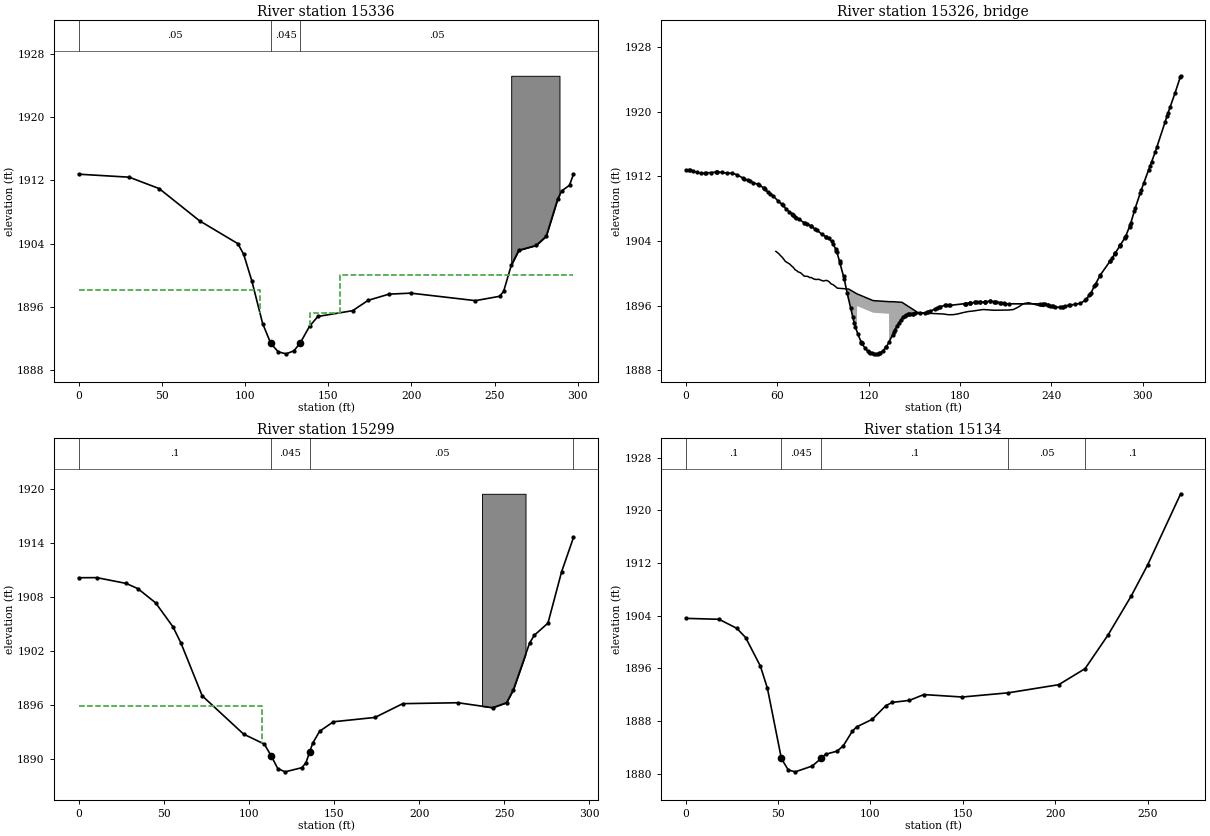
Type RM Length L Ch R = 1 ,15336   ,38.4,37.3,37.5
XS GIS Cut Line= 6
2023556.02215329305261.7883089182023509.93218321305247.156572385
2023469.69490774305222.2826202782023441.89460833305184.240105292
 2023440.1245644305180.5743159432023341.74630475305066.605828495
#Sta/Elev= 30
       0 1912.77    30.4 1912.39    48.4 1910.95    72.7 1906.87    95.7 1903.98
    99.2 1902.63   104.1 1899.27   110.6 1893.87   115.51891.353     120 1890.29
   124.7 1890.04   129.4 1890.42   133.31891.458   138.8 1893.53   143.8 1894.77
   164.7  1895.5     174 1896.81   186.5 1897.59   199.6 1897.72   238.5 1896.77
     253 1897.32   255.4 1897.94     260 1901.24   264.5 1903.14   274.9 1903.75
     281 1904.92   287.9 1909.62   290.3 1910.65     295 1911.37   297.4 1912.78
#Mann= 3 ,-1 , 0
       0     .05       0   115.5    .045       0   133.3     .05       0
#XS Ineff= 3 ,-1
       0     109 1898.06     139     157 1895.25     157     300    1900
Permanent Ineff=
       F       F       F
#Block Obstruct= 1 ,-1
  259.96  288.98 1925.22
Bank Sta=115.5,133.3
XS Rating Curve= 0 ,0
Exp/Cntr(USF)=0,0
Exp/Cntr=0.5,0.3

Type RM Length L Ch R = 3 ,15326   ,,,
BEGIN DESCRIPTION:
Priavte Driveway
Survey ID: MIC030
END DESCRIPTION:
Bridge Culvert--1,0,-1,-1, 0
Deck Dist Width WeirC Skew NumUp NumDn MinLoCord MaxHiCord MaxSubmerge Is_Ogee
9,11,2.6,0, 168, 168, , , 0.98, 0, 0,0,,
  59.187  61.061   62.22   62.22  63.445  65.426  65.426  65.828  66.077  66.077
   67.13  68.212  69.934  69.934  70.596  71.666  71.666  72.979  73.791  73.791
  75.363  77.232  77.648  77.648  77.746  77.905  77.905   80.13  81.505  81.505
  82.514  84.145  84.145  84.897  85.362  85.362  87.281  87.334   89.22   89.22
  89.664  90.384  90.384  92.048  93.077  93.077  93.114  93.114  94.412    95.4
    95.4   96.76   98.62   98.62  99.107  99.463  99.463     107   112.5   112.5
     123   133.5   133.5     136     142 152.281 152.701 152.701 153.153  155.45
 155.984 155.984 156.558 158.619 159.267 159.267 159.964 161.788  162.55  162.55
 163.369 164.957 165.833 165.833 166.775 168.126 169.116 169.116 170.181 171.295
 172.399 172.399 173.586 174.463 175.682 175.682 176.992 177.632 178.965 178.965
 180.397 180.801 182.248 182.248 183.803  183.97 185.531 185.531 187.139 187.208
 188.814 188.814 190.308 190.614 192.097 192.097 193.477 194.019  195.38  195.38
 196.646 197.425 198.663 198.663 199.814 200.831 201.946 201.946 202.983 204.236
 205.229 205.229 206.152 207.642 208.512 208.512 209.321 211.047 211.795 211.795
  212.49 214.453 215.078 215.078 215.659 217.858  218.36  218.36 218.828 221.264
 221.643 221.643 221.997 224.669 224.926 224.926 225.165 228.075 228.209 228.209
 228.334 231.481 231.492 231.492 231.503 231.807 231.807 234.672
1902.721 1902.441902.1911902.1911901.9711901.4741901.4741901.4271901.3841901.384
 1901.261901.1541900.8381900.8381900.7441900.4721900.4721900.3131900.1821900.182
1900.0761899.7411899.6781899.6781899.6771899.6541899.6541899.6221899.4681899.468
1899.4851899.2881899.288 1899.281899.2361899.236 1899.271899.2641899.1181899.118
1899.1051899.0511899.0511899.1311899.0861899.0861899.0871899.0871898.9181898.697
1898.6971898.5981898.3251898.3251898.2451898.1661898.1661898.0551897.4561897.456
 1896.631896.4941896.4941896.4941896.4161895.168 1895.16 1895.161895.1581895.117
1895.1151895.115 1895.111895.075 1895.07 1895.071895.0651895.0341895.0291895.029
1895.0271895.0171895.0151895.0151895.0051894.9831894.9731894.9731894.9461894.908
1894.8811894.8811894.8861894.8811894.8871894.8871894.9311894.9461894.9921894.992
1895.0611895.0781895.1491895.149 1895.211895.2171895.2781895.2781895.3091895.311
1895.3431895.3431895.3881895.3981895.4431895.4431895.4771895.4911895.5251895.525
1895.5091895.4991895.4831895.4831895.474 1895.45 1895.44 1895.441895.446 1895.44
1895.4441895.4441895.4531895.4591895.4671895.4671895.4661895.4571895.4561895.456
1895.4681895.5131895.5251895.5251895.5691895.7891895.8281895.828 1895.881896.197
1896.2391896.239 1896.261896.3541896.3691896.3691896.3651896.2111896.2091896.209
1896.2051896.0311896.0311896.0311896.0311896.0191896.0191895.913
                                                                                
                                                                                
                                                                                
                                                                                
                                                                                
                                                                        1895.956
 1895.131894.994
                                                                                
                                                                                
                                                                                
                                                                                
                                                                                
                                                                                
                                                                                
                                                                                
                                                                                
                                                                
  59.187  61.061   62.22   62.22  63.445  65.426  65.426  65.828  66.077  66.077
   67.13  68.212  69.934  69.934  70.596  71.666  71.666  72.979  73.791  73.791
  75.363  77.232  77.648  77.648  77.746  77.905  77.905   80.13  81.505  81.505
  82.514  84.145  84.145  84.897  85.362  85.362  87.281  87.334   89.22   89.22
  89.664  90.384  90.384  92.048  93.077  93.077  93.114  93.114  94.412    95.4
    95.4   96.76   98.62   98.62  99.107  99.463  99.463     107   112.5   112.5
     123   133.5   133.5     136     142 152.281 152.701 152.701 153.153  155.45
 155.984 155.984 156.558 158.619 159.267 159.267 159.964 161.788  162.55  162.55
 163.369 164.957 165.833 165.833 166.775 168.126 169.116 169.116 170.181 171.295
 172.399 172.399 173.586 174.463 175.682 175.682 176.992 177.632 178.965 178.965
 180.397 180.801 182.248 182.248 183.803  183.97 185.531 185.531 187.139 187.208
 188.814 188.814 190.308 190.614 192.097 192.097 193.477 194.019  195.38  195.38
 196.646 197.425 198.663 198.663 199.814 200.831 201.946 201.946 202.983 204.236
 205.229 205.229 206.152 207.642 208.512 208.512 209.321 211.047 211.795 211.795
  212.49 214.453 215.078 215.078 215.659 217.858  218.36  218.36 218.828 221.264
 221.643 221.643 221.997 224.669 224.926 224.926 225.165 228.075 228.209 228.209
 228.334 231.481 231.492 231.492 231.503 231.807 231.807 234.672
1902.721 1902.441902.1911902.1911901.9711901.4741901.4741901.4271901.3841901.384
 1901.261901.1541900.8381900.8381900.7441900.4721900.4721900.3131900.1821900.182
1900.0761899.7411899.6781899.6781899.6771899.6541899.6541899.6221899.4681899.468
1899.4851899.2881899.288 1899.281899.2361899.236 1899.271899.2641899.1181899.118
1899.1051899.0511899.0511899.1311899.0861899.0861899.0871899.0871898.9181898.697
1898.6971898.5981898.3251898.3251898.2451898.1661898.1661898.0551897.4561897.456
 1896.631896.4941896.4941896.4941896.4161895.168 1895.16 1895.161895.1581895.117
1895.1151895.115 1895.111895.075 1895.07 1895.071895.0651895.0341895.0291895.029
1895.0271895.0171895.0151895.0151895.0051894.9831894.9731894.9731894.9461894.908
1894.8811894.8811894.8861894.8811894.8871894.8871894.9311894.9461894.9921894.992
1895.0611895.0781895.1491895.149 1895.211895.2171895.2781895.2781895.3091895.311
1895.3431895.3431895.3881895.3981895.4431895.4431895.4771895.4911895.5251895.525
1895.5091895.4991895.4831895.4831895.474 1895.45 1895.44 1895.441895.446 1895.44
1895.4441895.4441895.4531895.4591895.4671895.4671895.4661895.4571895.4561895.456
1895.4681895.5131895.5251895.5251895.5691895.7891895.8281895.828 1895.881896.197
1896.2391896.239 1896.261896.3541896.3691896.3691896.3651896.2111896.2091896.209
1896.2051896.0311896.0311896.0311896.0311896.0191896.0191895.913
                                                                                
                                                                                
                                                                                
                                                                                
                                                                                
                                                                        1895.956
 1895.131894.994
                                                                                
                                                                                
                                                                                
                                                                                
                                                                                
                                                                                
                                                                                
                                                                                
                                                                                
                                                                
BR Coef=-1 , 1 , 0 ,, 0 ,,,0.8,0,1.2,0,
WSPro=,,,, 1 ,,,, 0 ,,,, 0 ,,,,-1 ,-1 ,-1 , 0 , 0 , 0 , 0 , 0
BR U #Sta/Elev= 196
       0 1912.77     1.9 1912.79     2.8 1912.77     4.5 1912.69     7.1 1912.51
     9.8 1912.38    12.4  1912.4    13.2 1912.43    16.6 1912.47    20.1 1912.55
    20.2 1912.55    20.7 1912.55    23.5  1912.5    26.9  1912.4    30.4 1912.39
    33.8  1912.2    37.3 1911.81    38.5 1911.72    40.7 1911.51    42.4 1911.39
    44.2 1911.22    47.6    1911    48.4 1910.95    51.1 1910.56    51.4 1910.51
    51.7 1910.45    53.7  1910.1    55.2 1909.84    57.4  1909.6    60.8 1908.91
    62.9 1908.59    63.6 1908.47    65.6 1908.02      68  1907.6    69.9 1907.35
    70.3 1907.26    70.6 1907.21    71.9 1907.01    72.7 1906.87    74.5 1906.68
    77.5 1906.29    78.4 1906.24    79.9 1906.07      82 1905.89    82.2 1905.87
    84.6 1905.53    86.1 1905.36    89.4 1904.83    91.8 1904.55    92.1 1904.51
    93.8 1904.32    95.7 1903.98    96.6 1903.69    98.5 1902.99    98.9  1902.8
    99.2 1902.63     101 1901.48   101.2  1901.3   103.6 1899.65   104.1 1899.27
   105.9 1897.62   108.3 1895.68   109.6  1894.6   110.6 1893.87   111.4 1893.36
     113 1892.49   115.2 1891.46   115.3 1891.41   115.4 1891.38   115.51891.353
   117.7 1890.76   119.5 1890.37     120 1890.29   120.8  1890.2   122.4  1890.1
   123.6 1890.05   124.7 1890.04   126.3 1890.06   127.1  1890.1   127.6 1890.15
   129.4 1890.42   131.7 1890.88   131.8 1890.91   133.31891.458   135.8 1892.37
   136.5 1892.69   137.4 1893.02   138.8 1893.53   139.8 1893.81   141.2 1894.23
   142.8 1894.58   143.8 1894.77   144.4 1894.81     146 1894.95   146.9 1894.99
   147.4 1895.02   148.9 1895.03   149.1 1895.03   150.6 1895.04   153.9 1895.04
   157.2 1895.09   158.4 1895.16   159.3 1895.22   160.5 1895.29   163.8 1895.62
   164.7 1895.69   166.1 1895.81   167.1 1895.89   170.3 1896.03   171.1 1896.03
   172.9 1896.04   173.6 1896.04   183.2 1896.25   183.5 1896.25   183.7 1896.26
   186.6 1896.35   186.7 1896.36   186.9 1896.36     190  1896.4   190.1  1896.4
   191.3 1896.41   193.3 1896.41   193.4 1896.41   196.4  1896.5   196.6 1896.51
   196.8 1896.51   199.6 1896.54   199.9 1896.54   202.7 1896.51   203.2  1896.5
   203.6 1896.49   206.4 1896.38     207 1896.36   209.1 1896.28   209.7 1896.25
   212.2 1896.23   232.7 1896.22   234.3  1896.2   234.4  1896.2     236 1896.17
   237.6 1896.09   237.7 1896.09   239.3 1896.01   240.7 1895.94   241.1 1895.92
   242.6 1895.85   245.8 1895.79   247.1 1895.83   247.9 1895.87   249.1 1895.92
   251.4 1896.04   252.4 1896.09   255.7 1896.16     259 1896.29   262.3 1896.65
   262.9 1896.77     265 1897.32   265.5 1897.43   266.1 1897.57   268.4 1898.46
   268.8 1898.58   269.2 1898.71   271.8 1899.65   272.1 1899.76   278.7 1901.52
   278.7 1901.53     280  1901.9   281.9 1902.45     282 1902.47     282 1902.49
   285.1 1903.42   285.2 1903.47   285.4 1903.52   288.2 1904.37   288.5 1904.44
   288.9  1904.6   291.4 1905.78   291.8 1905.97   292.3 1906.26   294.6  1907.7
   295.1 1908.04   298.4 1909.94   299.1  1910.3   300.9 1911.24     304 1912.81
   304.9 1913.26   305.9 1913.77   308.2 1914.97   309.3 1915.59   314.8 1918.77
   316.1 1919.51   316.7 1919.84   318.1  1920.6   321.4 1922.37   324.6 1924.24
     325 1924.45
BR U #Mann= 4
       0     .05   115.5     .04   133.3     .05   298.4      .1
BR D #Sta/Elev= 196
       0 1910.16     3.8 1910.25     6.4 1910.25    10.7 1910.17    14.2 1910.07
    24.5 1909.71    27.9 1909.53    31.4 1909.27    32.5 1909.15    34.8 1908.95
    38.3  1908.5    40.4 1908.15    41.7 1907.95      43 1907.72    44.3 1907.53
    45.2 1907.38    47.1 1907.03    48.6 1906.67    50.6 1906.14    52.5  1905.6
    53.8 1905.29    55.4 1904.72    56.3 1904.34    60.1 1902.92    62.5 1901.65
    64.1 1900.88    64.9 1900.46    66.3 1899.84    67.9 1899.09    71.8 1897.33
    72.1 1897.21    72.6 1897.05    74.5 1896.62    75.6 1896.38    76.8 1896.19
    78.8 1895.88    79.2 1895.83    79.5 1895.78    80.6 1895.55    83.3 1894.99
      84 1894.91    86.4 1894.55    91.1 1893.65    91.3 1893.63    93.5 1893.38
    94.9  1893.2    95.7 1893.13    96.9  1892.8   100.1 1892.41   100.6 1892.35
   100.9  1892.3   102.9 1892.24     105 1892.15   105.3 1892.14   105.7 1892.11
   107.6 1891.91   109.1 1891.69     110 1891.47   111.3 1891.11   112.3 1890.73
   113.1 1890.39   114.7 1889.77     117 1888.97   117.2 1888.93   119.4 1888.69
   121.3 1888.61   121.7 1888.61   122.4 1888.63   125.3 1888.66   126.4  1888.7
   127.9 1888.79   128.8  1888.8   129.4 1888.81   131.1 1889.07   133.3 1889.56
   133.5  1889.6   133.5 1889.62   135.8 1890.85   137.5 1891.79   138.2 1892.05
   139.1 1892.35   140.5 1892.84   141.6 1893.12   142.8 1893.28   142.9 1893.28
     144 1893.35   145.1 1893.42   147.5 1893.49   148.4 1893.53   149.2 1893.53
   150.9  1893.5   151.7  1893.5   152.4  1893.5   154.3 1893.49   154.9 1893.49
   155.6  1893.5   157.7  1893.5   161.5 1893.63   164.5 1893.66   168.1 1893.63
   171.3 1893.71   177.9 1893.98   178.1 1893.99   180.9 1894.13   181.2 1894.14
   181.5 1894.14   184.1 1894.14   184.5 1894.14     191 1894.02   191.7 1894.01
   193.6 1893.98   194.3 1893.98   195.1 1893.99   196.8 1894.01   197.6 1894.01
   198.5 1894.03   199.9 1894.06   204.2  1894.2   210.7 1894.48   212.2 1894.56
   212.6 1894.58     214 1894.66   217.3 1894.86   218.9 1894.91     219 1894.92
   220.6 1894.97   222.1 1895.04   222.4 1895.05   223.9 1895.11   227.2  1895.3
   228.4 1895.42   229.2 1895.48   230.4 1895.59   231.6 1895.74   232.6 1895.86
     237 1896.53     238 1896.66   239.4 1896.85   240.3 1896.98   241.1 1897.05
   242.8 1897.19   243.6 1897.26   244.3  1897.3   246.2 1897.41   246.9 1897.44
   247.5 1897.48   249.6 1897.62   250.1 1897.65   253.8 1898.08   256.4 1898.46
   256.7 1898.49     257 1898.53   259.8 1898.97     260 1898.99   266.6 1900.27
   266.6 1900.28   269.6  1900.9   269.8 1900.95   270.1 1901.01   273.1 1901.84
     276 1902.86   276.4 1903.02   276.9  1903.2   279.1 1904.22   279.7 1904.43
   280.3  1904.7   282.3 1905.74     283 1906.04   283.7 1906.43   285.5  1907.4
   286.3 1907.83   287.1 1908.32   288.7 1909.22   289.5 1909.74   290.5 1910.27
   291.8    1911   292.8 1911.55     295 1912.49   296.1 1912.96   299.4  1914.4
   302.7 1916.08   309.2 1919.68   310.8  1920.6   310.9 1920.65   312.5 1921.57
     314 1922.45   314.3 1922.63   315.8  1923.5   317.2 1924.31   317.7 1924.64
   319.1 1925.44   320.3 1926.23   321.1 1926.73   322.4  1927.5   323.5 1928.22
 325.795 1929.64
BR D #Mann= 4
       0      .1   113.1     .04   135.8     .05   290.5      .1
BC Design=,, 0 ,, 0 ,,,,,,
BC Use User HTab Curves=0
BC User HTab FreeFlow(D)= 0

Type RM Length L Ch R = 1 ,15299   ,160.4,164.2,161.9
XS GIS Cut Line= 5
2023586.50332971305240.2425984472023540.41335963305225.610861914
2023500.17608416305200.7369098082023472.37578475305162.694394821
2023384.97188029305043.298820528
#Sta/Elev= 30
       0 1910.16    10.7 1910.17    27.9 1909.53    34.8 1908.95    45.2 1907.38
    55.4 1904.72    60.1 1902.92    72.6 1897.05    96.9  1892.8   109.1 1891.69
   113.1 1890.39     117 1888.97   121.3 1888.61   131.1 1889.07   133.5  1889.6
   135.8 1890.85   137.5 1891.79   141.6 1893.12   149.7 1894.17   174.1 1894.65
   190.4 1896.18   222.9 1896.28   243.2 1895.73   251.4 1896.29   255.4 1897.74
   264.9  1902.9   267.6 1903.76   275.7 1905.12   283.7 1910.81   290.7 1914.63
#Mann= 4 ,-1 , 0
       0      .1       0   113.1    .045       0   135.8     .05       0
   290.5      .1       0
#XS Ineff= 2 , 0
             108  1895.9     140            1892
Permanent Ineff=
       F       F
#Block Obstruct= 1 ,-1
  236.93  262.52 1919.48
Bank Sta=113.1,135.8
XS Rating Curve= 0 ,0
Exp/Cntr(USF)=0,0
Exp/Cntr=0.5,0.3

Type RM Length L Ch R = 1 ,15134   ,203.1,199.9,192.9
XS GIS Cut Line= 3
2023670.74664852305192.183064526 2023615.6822612  305095.8203867
2023519.31958337 304971.92551521
#Sta/Elev= 30
       0 1903.61      18 1903.47    27.6  1902.1    32.4  1900.7    40.4 1896.35
    44.2 1892.99    51.7 1882.41    51.7 1882.34    55.5 1880.57    59.3 1880.29
    68.5 1881.18    73.3 1882.33    75.7 1882.96      82 1883.44    85.3 1884.26
    90.1 1886.43    92.5 1887.12   100.9 1888.26   108.4 1890.36   111.8 1890.84
   121.1 1891.15   128.9 1892.03   149.7 1891.66   174.7  1892.3   201.9 1893.53
   216.2 1895.97   228.7 1901.12   241.2 1907.02     250 1911.69267.9435 1922.54
#Mann= 5 ,-1 , 0
       0      .1       0    51.7    .045       0    73.3      .1       0
   174.7     .05       0   216.2      .1       0
Bank Sta=51.7,73.3
XS Rating Curve= 0 ,0
Exp/Cntr(USF)=0,0
Exp/Cntr=0.3,0.1