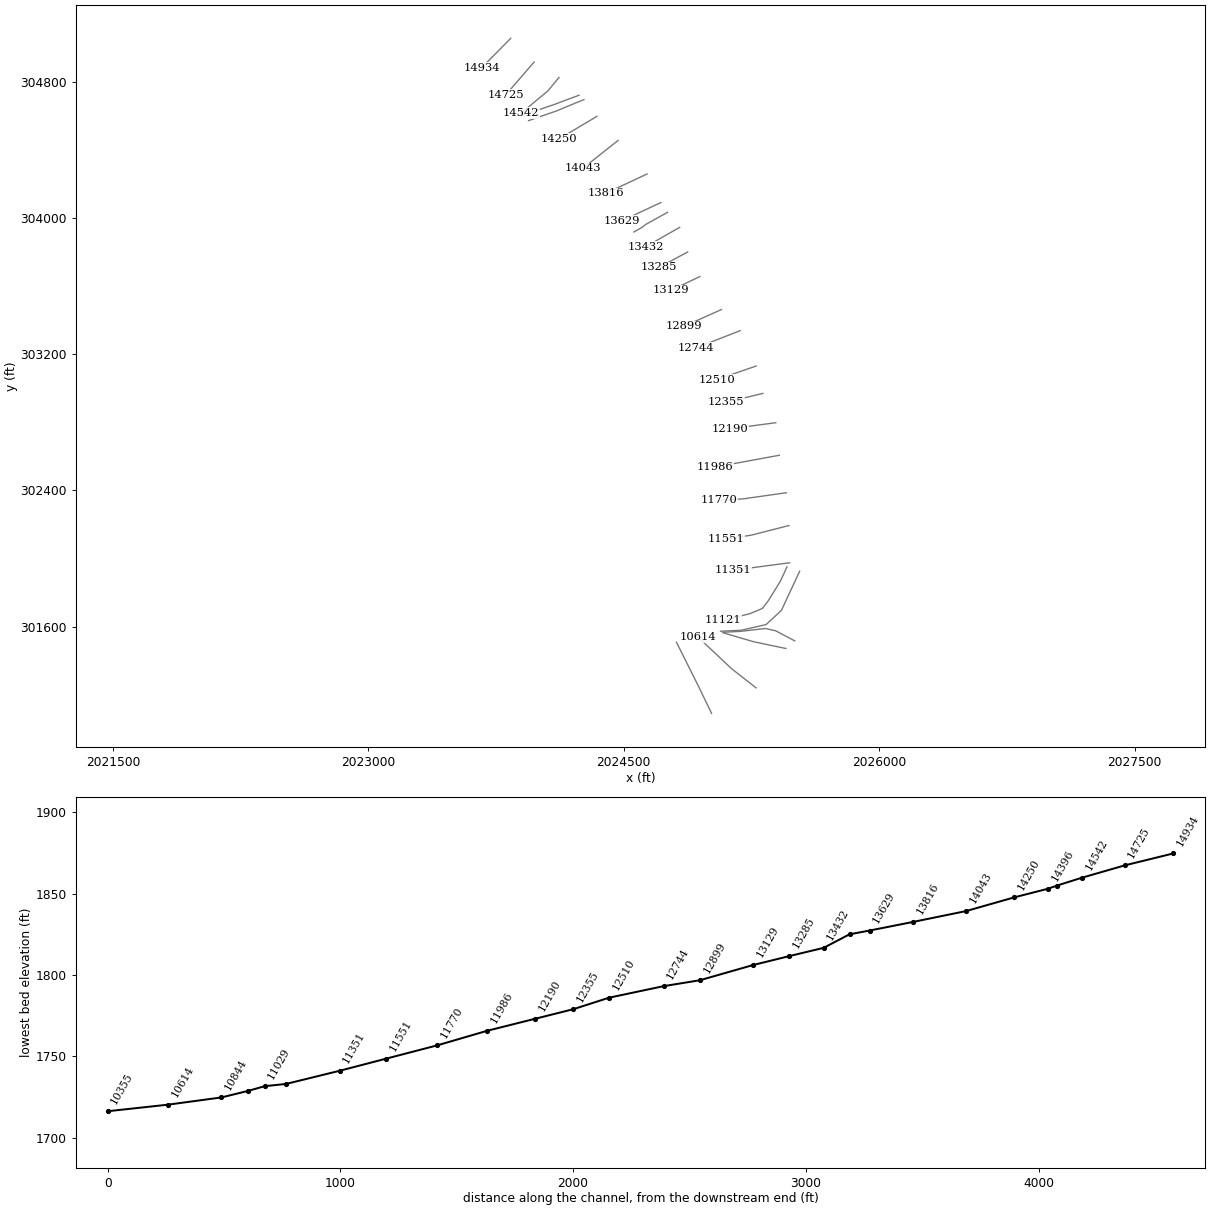
HEC-RAS study MILLCK.prj: MILLCK

--- MILLCK.g01 (geometry) --- (continued)

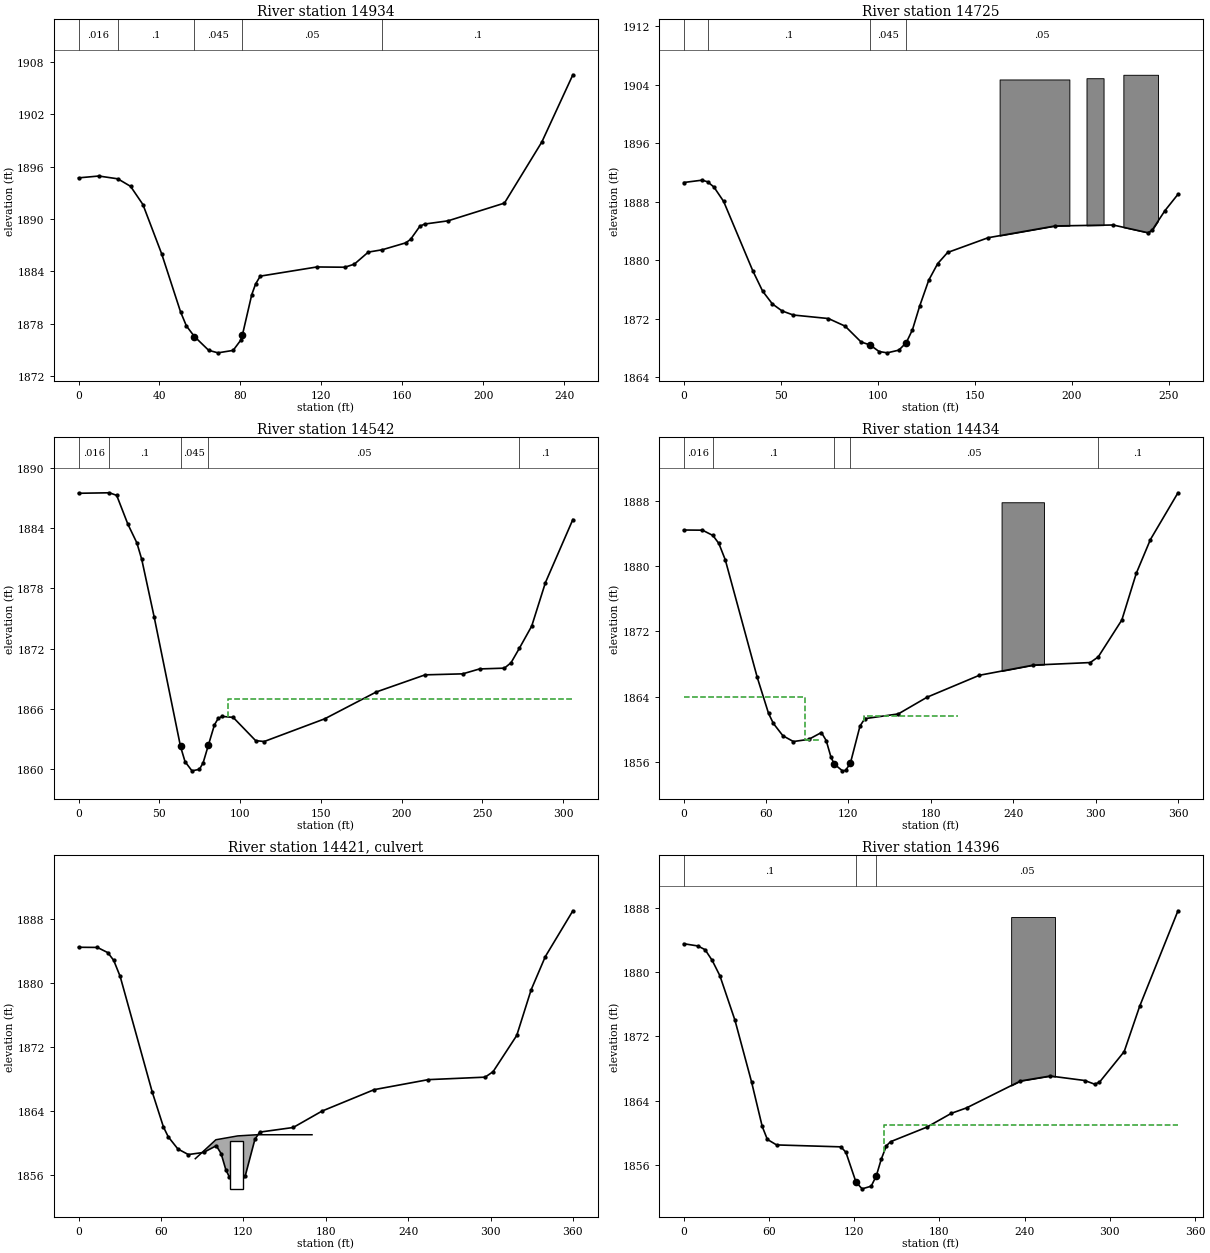
Type RM Length L Ch R = 1 ,14934   ,208.5,209.3,209.8
XS GIS Cut Line= 3
2023835.93981051 305057.27531557  2023738.200523304958.159418377
2023663.86360011304883.822495483
#Sta/Elev= 30
       0  1894.7      10 1894.91    19.4 1894.59    25.7 1893.73    31.8 1891.65
    41.1 1885.99    50.4 1879.37    53.3 1877.75    57.3 1876.53    64.3 1874.96
    68.9 1874.67    76.4 1874.95    80.1  1876.1      81 1876.73    85.6 1881.33
    87.5 1882.55    89.8 1883.45   117.8  1884.5   131.6 1884.47   136.3 1884.82
   143.2  1886.2   150.1 1886.47   161.7 1887.26   164.1 1887.66   168.7 1889.16
     171 1889.41   182.6 1889.78   210.5 1891.81     229 1898.81244.3293  1906.5
#Mann= 5 ,-1 , 0
       0    .016       0    19.4      .1       0    57.3    .045       0
      81     .05       0   150.1      .1       0
Bank Sta=57.3,81
XS Rating Curve= 0 ,0
Exp/Cntr(USF)=0,0
Exp/Cntr=0.3,0.1

Type RM Length L Ch R = 1 ,14725   ,182,182.9,184.9
XS GIS Cut Line= 2
2023973.60077883304918.2377375642023807.03100716304725.512381912
#Sta/Elev= 30
       0 1890.61     9.5 1890.93    12.3 1890.71    15.6 1889.99    20.6 1888.02
    35.6 1878.55    40.7 1875.75    45.7 1874.01    50.7 1873.05    56.5 1872.49
    74.6 1872.01    83.2 1870.97    91.4 1868.81    96.1 1868.39   100.7  1867.5
   104.9 1867.32   110.9 1867.69   114.7 1868.71   117.9 1870.48   121.6  1873.7
   126.3 1877.26   130.9 1879.52     136 1881.04   156.9 1883.06   191.4 1884.67
   221.3  1884.8   239.3 1883.74   241.4 1884.09     248 1886.76254.7323    1889
#Mann= 4 ,-1 , 0
       0    .016       0    12.3      .1       0    96.1    .045       0
   114.7     .05       0
#Block Obstruct= 3 ,-1
  162.81  198.76  1904.7  207.59  216.38 1904.87  226.59  244.43 1905.34
Bank Sta=96.1,114.7
XS Rating Curve= 0 ,0
Exp/Cntr(USF)=0,0
Exp/Cntr=0.3,0.1

Type RM Length L Ch R = 1 ,14542   ,114.6,108.1,101.3
XS GIS Cut Line= 3
2024119.52140526304827.3814984712024054.82075014304748.914746527
2023897.88724626304618.136826621
#Sta/Elev= 30
       0 1887.51    19.1 1887.56    23.6  1887.3    30.5 1884.43    36.1 1882.55
    39.1 1880.91    46.8 1875.15    63.1 1862.22    65.9  1860.7    70.2 1859.78
    74.8 1859.93    77.1 1860.58    80.4 1862.37    84.1 1864.37    86.4 1865.01
    88.8 1865.22    95.7 1865.12   109.6  1862.8   114.9 1862.71   152.4 1864.98
   184.3 1867.66   214.5 1869.37   237.8 1869.47   248.2 1869.96   263.6 1870.04
   267.7 1870.58   272.8 1872.01   280.5 1874.24     289 1878.59305.9832 1884.89
#Mann= 5 ,-1 , 0
       0    .016       0    19.1      .1       0    63.1    .045       0
    80.4     .05       0   272.8      .1       0
#XS Ineff= 2 , 0
                           92.28            1867
Permanent Ineff=
       F       F
Bank Sta=63.1,80.4
XS Rating Curve= 0 ,0
Exp/Cntr(USF)=0,0
Exp/Cntr=0.5,0.3

Type RM Length L Ch R = 1 ,14434   ,38,38.5,39
XS GIS Cut Line= 3
2024237.80269266304723.1800975472024093.29171455304668.988480757
2023898.60331349304602.754282459
#Sta/Elev= 30
       0 1884.42    13.7  1884.4    21.3 1883.75    25.6 1882.78    30.3 1880.77
    53.6 1866.36    61.8 1861.97    65.3 1860.74    72.3 1859.22    79.9 1858.52
      91 1858.78   100.3 1859.62   103.8 1858.64   107.3 1856.59   109.7 1855.76
   115.6 1854.93   117.9 1854.98   121.4 1855.86   128.4 1860.41   131.9 1861.32
   156.3  1861.9   177.3 1863.95   215.3 1866.63   254.7 1867.88   296.1 1868.19
   301.9 1868.88   319.1  1873.4   329.6 1879.11   339.9 1883.25359.9844 1888.98
#Mann= 5 ,-1 , 0
       0    .016       0    21.3      .1       0   109.7    .045       0
   121.4     .05       0   301.9      .1       0
#XS Ineff= 3 ,-1
       0      88    1864      88      99 1858.73     131     200  1861.7
Permanent Ineff=
       F       F       F
#Block Obstruct= 1 ,-1
  231.51  262.38 1887.82
Bank Sta=109.7,121.4
XS Rating Curve= 0 ,0
Exp/Cntr(USF)=0,0
Exp/Cntr=0.5,0.3

Type RM Length L Ch R = 2 ,14421   ,,,
BEGIN DESCRIPTION:
Private Driveway
Survey ID: MIC020
END DESCRIPTION:
Bridge Culvert--1,0,-1,-1, 0
Deck Dist Width WeirC Skew NumUp NumDn MinLoCord MaxHiCord MaxSubmerge Is_Ogee
11,12,2.6,0, 5, 5, , , 0.98, 0, 0,0,,
      85     100     116     130     170
    18581860.3691860.8511860.9941860.994
                                        
      85     114     128     144     170
    18581860.3691860.8511860.9941860.994
                                        
BR Coef=-1 , 1 , 0 ,, 0 ,,,0.8,0,1.2,0,
WSPro=,,,, 1 ,,,, 0 ,,,, 0 ,,,,-1 ,-1 ,-1 , 0 , 0 , 0 , 0 , 0
Culvert=2,6,10,12,0.012,0.2,1,8,1,1854.234,115,1853.849,128,Culvert #1  , 0 ,11
     115     128
BC Culvert Barrel=1,Barrel1,0
Culvert Bottom n=0.012
BC Design=,, 0 ,, 0 ,,,,,,
BC Use User HTab Curves=0
BC User HTab FreeFlow(D)= 0

Type RM Length L Ch R = 1 ,14396   ,142.2,145.1,144.8
XS GIS Cut Line= 4
2024265.90204951304697.0878376112024167.55430052304656.945899249
2024111.35558682304632.8607362312023940.75234877304573.651377146
#Sta/Elev= 30
       0 1883.57      10 1883.29    15.1 1882.82    20.1 1881.48    25.5 1879.57
    36.1 1874.02    47.8 1866.31    55.3 1860.76    58.9 1859.15    65.4 1858.46
   110.7 1858.22   114.2 1857.54   121.3 1853.82   125.6 1852.98     132 1853.31
   135.6  1854.6   139.1 1856.69   142.7 1858.35   145.6 1858.86   171.2 1860.68
   188.5 1862.41   199.1 1863.08   237.1 1866.44     258 1867.06   282.3  1866.5
   289.3 1866.04   292.7 1866.29   310.1 1870.11     321 1875.77347.9527 1887.68
#Mann= 3 ,-1 , 0
       0      .1       0   121.3    .045       0   135.6     .05       0
#XS Ineff= 2 , 0
       0     116  1856.2     141       0    1861
Permanent Ineff=
       F       F
#Block Obstruct= 1 ,-1
  230.52  261.38  1886.9
Bank Sta=121.3,135.6
XS Rating Curve= 0 ,0
Exp/Cntr(USF)=0,0
Exp/Cntr=0.5,0.3

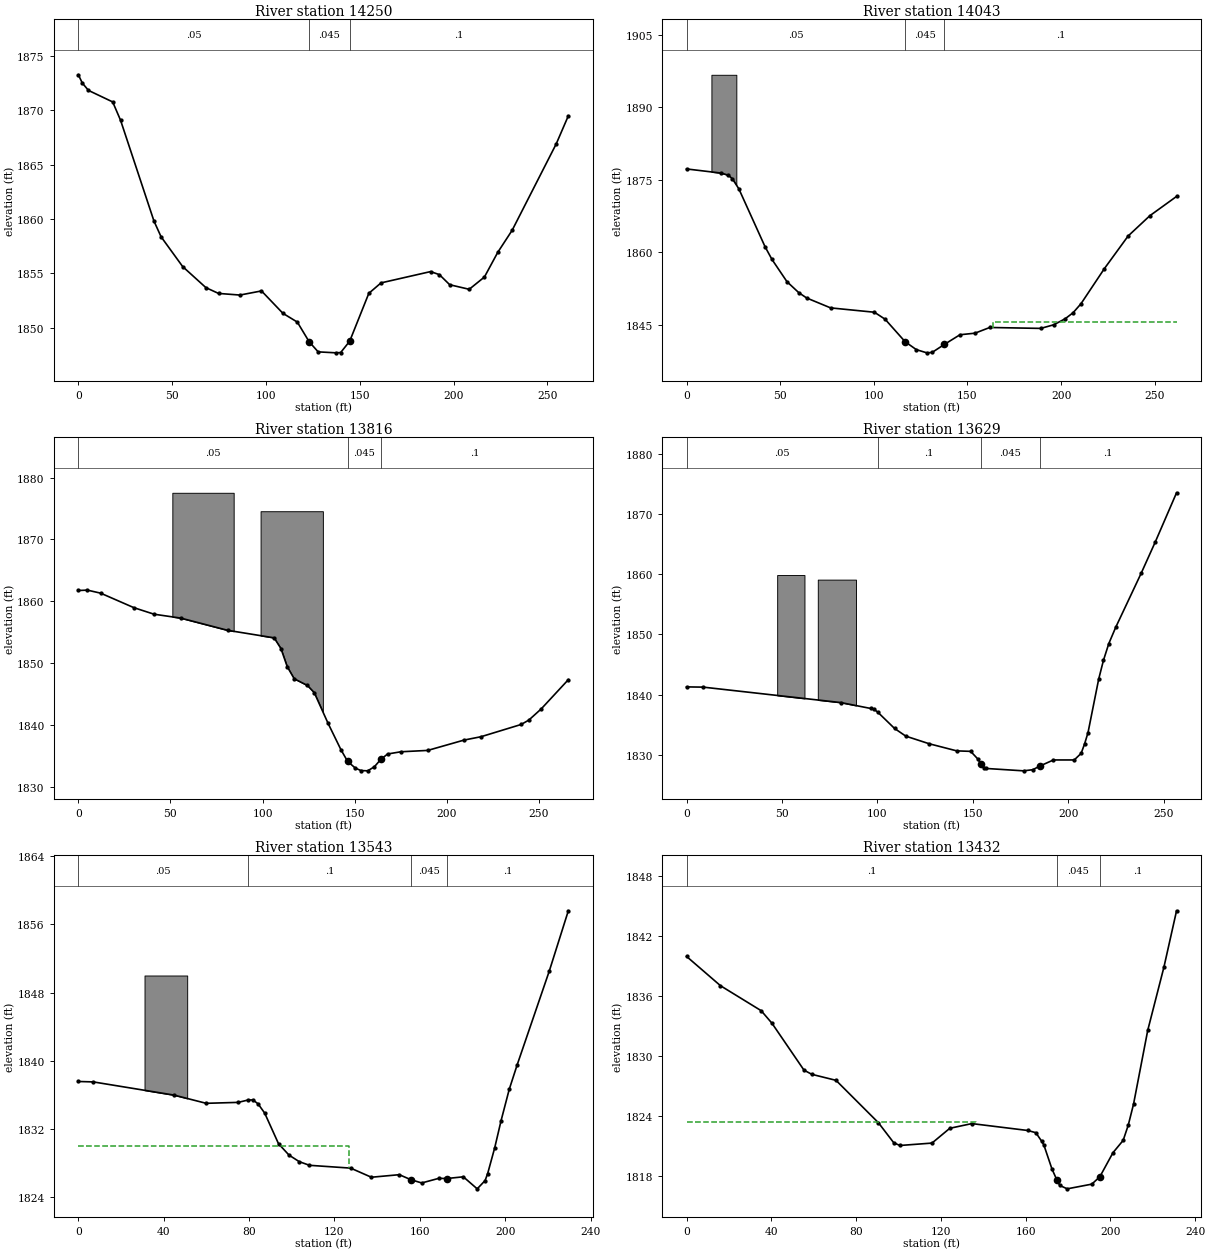
Type RM Length L Ch R = 1 ,14250   ,203.7,207.2,210.3
XS GIS Cut Line= 2
2024342.53217394304598.8642910562024118.14479557304465.333151783
#Sta/Elev= 30
       0 1873.28     2.1 1872.52     5.4 1871.84    18.3 1870.78    22.5 1869.09
    40.3 1859.81    44.1 1858.36    55.6 1855.62      68 1853.68    74.7 1853.15
    86.1    1853    97.6 1853.38     109 1851.32   116.7 1850.51     123  1848.7
   127.8 1847.77   137.4 1847.68   139.8 1847.71   144.6 1848.75   154.8 1853.16
   161.3 1854.12   187.7 1855.16   192.4 1854.88   197.9 1853.95   208.3 1853.53
   216.4 1854.66   223.5 1856.93   231.2 1858.97   254.7 1866.93261.1135  1869.5
#Mann= 3 ,-1 , 0
       0     .05       0     123    .045       0   144.6      .1       0
Bank Sta=123,144.6
XS Rating Curve= 0 ,0
Exp/Cntr(USF)=0,0
Exp/Cntr=0.3,0.1

Type RM Length L Ch R = 1 ,14043   ,229,226.9,220.5
XS GIS Cut Line= 2
2024466.42704543304457.0734936832024261.31220263304294.633551063
#Sta/Elev= 30
       0 1877.25    18.6 1876.39    22.3 1875.95    24.5 1875.19    27.9 1873.15
    41.9 1861.18    45.6 1858.55    53.6 1853.96    59.9 1851.69    64.1 1850.59
    76.9 1848.54   100.3 1847.64     106  1846.2   116.7 1841.55   122.7 1839.91
   128.3 1839.25   131.1 1839.33   137.7    1841     146 1842.99     154 1843.31
   161.9 1844.49   189.1  1844.3   196.1 1845.05   202.2  1846.3   206.4 1847.54
   210.6 1849.39   223.1 1856.65   235.8  1863.4   247.4 1867.59261.6464 1871.57
#Mann= 3 ,-1 , 0
       0     .05       0   116.7    .045       0   137.7      .1       0
#XS Ineff= 2 , 0
                          163.44         1845.57
Permanent Ineff=
       F       F
#Block Obstruct= 1 ,-1
   13.26   26.57 1896.71
Bank Sta=116.7,137.7
XS Rating Curve= 0 ,0
Exp/Cntr(USF)=0,0
Exp/Cntr=0.3,0.1

Type RM Length L Ch R = 1 ,13816   ,187.3,187.1,186.5
XS GIS Cut Line= 2
2024637.12664615304260.2183089822024396.21995158304147.336314958
#Sta/Elev= 30
       0 1861.75     4.9 1861.81    12.1 1861.32    30.2 1858.97    41.1 1857.92
    55.6 1857.29      81 1855.32   106.3  1854.1     110 1852.37   113.4 1849.45
   117.2 1847.49   124.4  1846.4   128.1 1845.24   135.6 1840.28   142.6 1836.01
   146.2 1834.14   150.4 1833.05   153.4 1832.66   157.1 1832.61   160.7 1833.26
   164.3 1834.48   167.9 1835.33   175.1 1835.69   189.7 1835.91   209.4 1837.58
   218.6 1838.12   240.4  1840.1   244.6 1840.81   251.3 1842.61266.0421 1847.34
#Mann= 3 ,-1 , 0
       0     .05       0   146.2    .045       0   164.3      .1       0
#Block Obstruct= 2 ,-1
   51.03   84.33 1877.54   98.94  132.77 1874.56
Bank Sta=146.2,164.3
XS Rating Curve= 0 ,0
Exp/Cntr(USF)=0,0
Exp/Cntr=0.3,0.1

Type RM Length L Ch R = 1 ,13629   ,81.4,86.8,89.7
XS GIS Cut Line= 2
2024718.34661746304092.2719276292024485.69958099303983.519762654
#Sta/Elev= 30
       0 1841.27     8.7 1841.23    80.9 1838.66    96.4 1837.69    98.2 1837.54
   100.1  1837.1     109 1834.36   114.9 1833.08   127.2 1831.81   141.6 1830.63
   148.9 1830.55   152.5 1829.33   154.3 1828.48   156.1 1827.77   156.8 1827.71
   176.6 1827.31   181.5  1827.5   185.1  1828.1   192.3 1829.12   203.2 1829.12
   206.8 1830.22   208.6 1831.78   210.4 1833.66     216 1842.57   218.5 1845.69
   221.3 1848.47   224.9 1851.16   238.3 1860.19   245.7  1865.4256.8106 1873.55
#Mann= 4 ,-1 , 0
       0     .05       0   100.1      .1       0   154.3    .045       0
   185.1      .1       0
#Block Obstruct= 2 ,-1
   47.48   61.79 1859.87   68.77   88.79 1859.11
Bank Sta=154.3,185.1
XS Rating Curve= 0 ,0
Exp/Cntr(USF)=0,0
Exp/Cntr=0.3,0.1

Type RM Length L Ch R = 1 ,13543   ,113.2,111,109.7
XS GIS Cut Line= 4
2024757.22225412304034.9198901952024628.85405114303963.381360408
2024606.12218186303945.3295818642024559.32127453303919.254790633
#Sta/Elev= 30
       0 1837.57       7 1837.52    44.9 1835.97    59.9 1835.01    74.9 1835.12
    79.4 1835.39    81.8 1835.41    84.2 1834.95    87.3 1833.87    93.8 1830.27
    98.7 1828.94   103.5 1828.17   108.3 1827.74   127.6 1827.41   137.3 1826.34
   150.4 1826.64   155.81826.055   160.9 1825.67   168.9 1826.21   172.6 1826.19
   180.4 1826.39   186.9 1824.98   190.6 1825.95   191.8 1826.77   195.1 1829.79
   198.1 1832.99   201.9 1836.64   205.6  1839.5   220.7 1850.54   229.6 1857.59
#Mann= 4 ,-1 , 0
       0     .05       0    79.4      .1       0   155.8    .045       0
   172.6      .1       0
#XS Ineff= 2 , 0
          126.76 1830.05
Permanent Ineff=
       F       F
#Block Obstruct= 1 ,-1
      31      51    1850
Bank Sta=155.8,172.6
XS Rating Curve= 0 ,0
Exp/Cntr(USF)=0,0
Exp/Cntr=0.3,0.1

Type RM Length L Ch R = 1 ,13432   ,147.5,146.9,145.9
XS GIS Cut Line= 2
2024828.47539212303946.3513012072024627.49037837303832.092697499
#Sta/Elev= 30
       0 1839.94      16 1837.01    35.2 1834.51    40.3 1833.25    55.4 1828.56
    59.1 1828.14    70.5 1827.54    90.5  1823.3    97.8 1821.28   100.7 1821.02
   115.8 1821.26   124.2 1822.74   134.6 1823.21     161 1822.52   164.8  1822.3
   167.5 1821.46   168.6 1821.06   172.4 1818.67   174.8 1817.53   176.1 1817.02
   179.6 1816.68   191.2 1817.15     195 1817.89   201.2  1820.3     206 1821.53
   208.4 1823.05   210.9 1825.16   217.6 1832.55   225.2 1838.84231.1926 1844.51
#Mann= 3 ,-1 , 0
       0      .1       0   174.8    .045       0     195      .1       0
#XS Ineff= 2 , 0
          136.62 1823.37
Permanent Ineff=
       F       F
Bank Sta=174.8,195
XS Rating Curve= 0 ,0
Exp/Cntr(USF)=0,0
Exp/Cntr=0.3,0.1

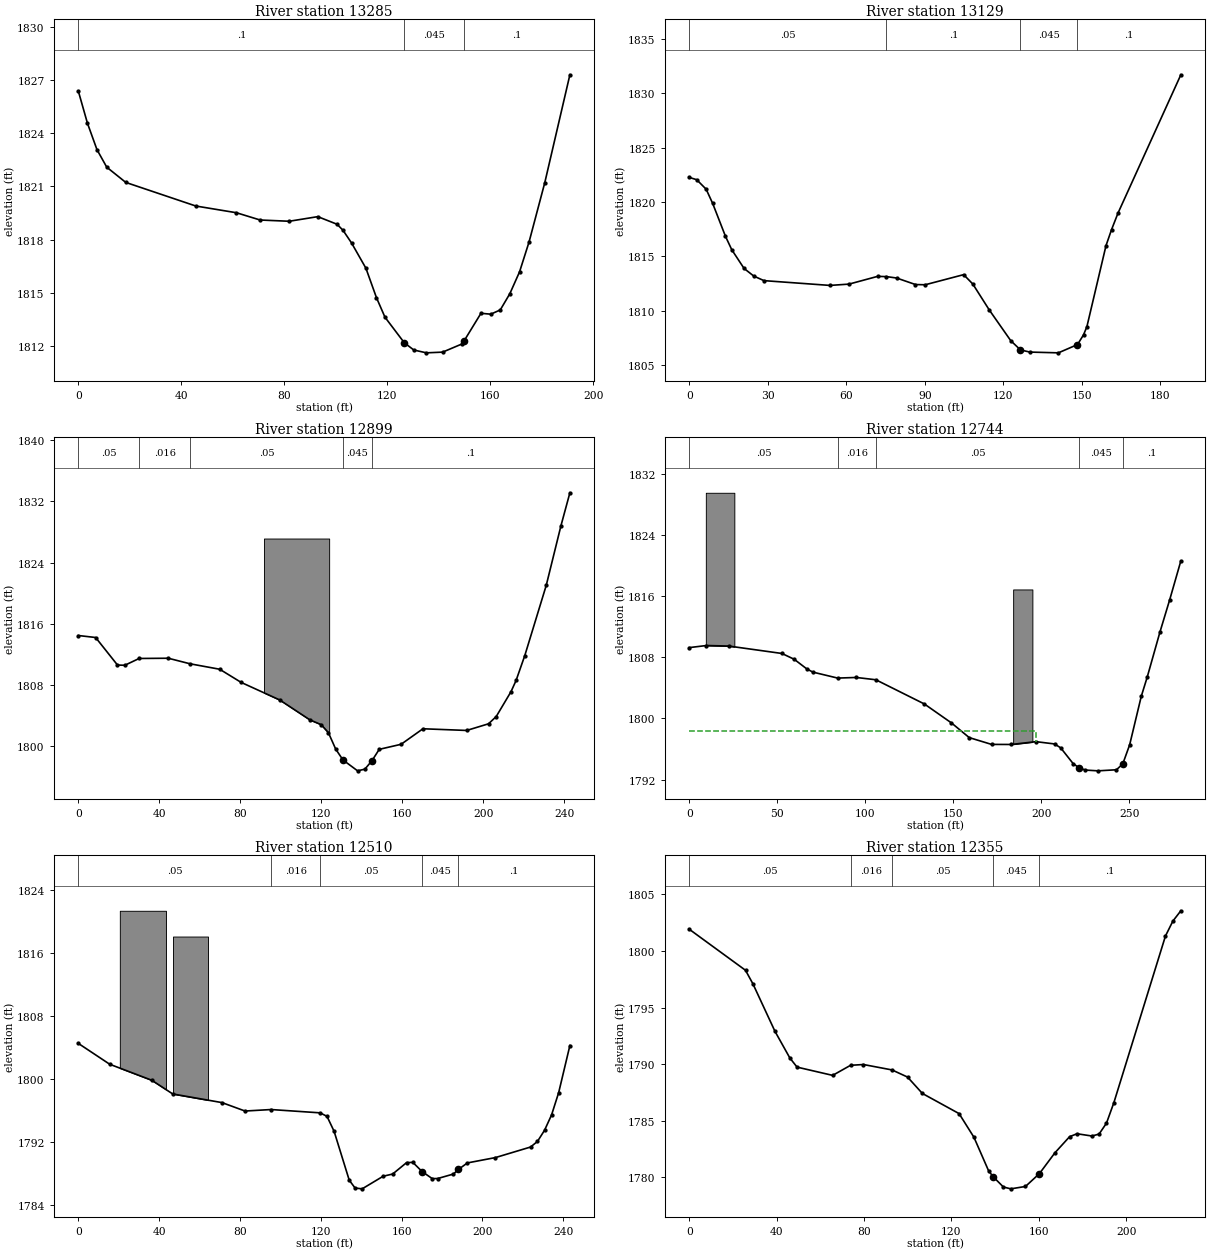
Type RM Length L Ch R = 1 ,13285   ,155.9,155.6,154.3
XS GIS Cut Line= 2
2024875.28012135303801.8072844682024707.33373999303710.951045375
#Sta/Elev= 30
       0 1826.36     3.5 1824.57     7.2 1823.08      11 1822.09    18.4 1821.23
    45.6  1819.9    61.4 1819.52    70.6 1819.11    81.9 1819.04      93  1819.3
   100.5 1818.87   102.8 1818.53   106.1 1817.82   111.7 1816.39   115.8 1814.73
   119.1 1813.63   126.6 1812.19   130.3 1811.78   135.2 1811.62   141.5 1811.66
     149 1812.12   149.7 1812.26   156.4 1813.85   160.2  1813.8   163.9 1814.04
   167.6 1814.95   171.4 1816.19   175.1 1817.88   181.2 1821.22190.9472  1827.3
#Mann= 3 ,-1 , 0
       0      .1       0   126.6    .045       0   149.7      .1       0
Bank Sta=126.6,149.7
XS Rating Curve= 0 ,0
Exp/Cntr(USF)=0,0
Exp/Cntr=0.3,0.1

Type RM Length L Ch R = 1 ,13129   ,228.9,229.5,228.5
XS GIS Cut Line= 2
2024946.86382487 303657.263267732024777.54083384303576.043296419
#Sta/Elev= 30
       0 1822.27     2.8 1822.06     6.4 1821.19     8.9 1819.88    13.8 1816.85
    16.2 1815.62    20.9  1813.9    24.6  1813.2    28.5 1812.78    53.7 1812.34
      61 1812.46    71.9 1813.17    75.3 1813.15    79.2 1813.02    86.4 1812.42
    90.1  1812.4   104.8 1813.33   108.3 1812.47   114.6 1810.08   122.8 1807.26
   126.5 1806.41   130.1 1806.21     141 1806.14   148.3  1806.9   150.6 1807.79
   151.9 1808.55   159.2    1816   161.3 1817.46   163.8    1819 187.795 1831.71
#Mann= 4 ,-1 , 0
       0     .05       0    75.3      .1       0   126.5    .045       0
   148.3      .1       0
Bank Sta=126.5,148.3
XS Rating Curve= 0 ,0
Exp/Cntr(USF)=0,0
Exp/Cntr=0.3,0.1

Type RM Length L Ch R = 1 ,12899   ,153.7,155.8,154.3
XS GIS Cut Line= 2
2025073.51191573303463.1613023952024851.87775673303364.045405203
#Sta/Elev= 30
       0 1814.46     8.5  1814.2    19.3  1810.6    22.9 1810.57      30 1811.46
    44.4 1811.49    55.2 1810.76    69.8 1810.05    80.4 1808.33    99.4 1806.04
   114.3 1803.44   119.9 1802.81   123.5 1801.75   127.1 1799.61   130.7 1798.19
   137.9 1796.77   141.5 1796.99     145 1798.09   148.6 1799.58   159.4 1800.24
   170.2 1802.27   191.8 1802.05   202.6 1802.92   206.4 1803.87   213.7 1807.12
   216.2 1808.58   220.5 1811.83   231.1 1821.01   238.4 1828.84242.7873 1833.12
#Mann= 5 ,-1 , 0
       0     .05       0      30    .016       0    55.2     .05       0
   130.7    .045       0     145      .1       0
#Block Obstruct= 1 ,-1
   91.65  123.86 1827.14
Bank Sta=130.7,145
XS Rating Curve= 0 ,0
Exp/Cntr(USF)=0,0
Exp/Cntr=0.3,0.1

Type RM Length L Ch R = 1 ,12744   ,236.4,234.1,231.3
XS GIS Cut Line= 2
2025183.64069039303339.2664309052024923.46146026303237.397314346
#Sta/Elev= 30
       0 1809.27     9.7 1809.54    22.4 1809.47    52.6  1808.5    59.6 1807.74
    66.7 1806.49    70.2 1806.06    84.3 1805.28    94.9 1805.36     106 1805.06
   133.6 1801.89     149 1799.41   159.1 1797.49   171.8  1796.6     183 1796.59
     197 1796.96   207.6 1796.66   211.1 1796.15   218.2 1794.08   221.7 1793.52
   225.2 1793.24   232.3 1793.14   242.8 1793.28   246.4 1794.05   250.3 1796.54
   256.9 1802.88   260.3 1805.41   267.5 1811.28   273.1 1815.55279.4111 1820.61
#Mann= 5 ,-1 , 0
       0     .05       0    84.3    .016       0     106     .05       0
   221.7    .045       0   246.4      .1       0
#XS Ineff= 2 , 0
          197.07 1798.34
Permanent Ineff=
       F       F
#Block Obstruct= 2 ,-1
    9.35   25.56 1829.53  184.07  195.01 1816.88
Bank Sta=221.7,246.4
XS Rating Curve= 0 ,0
Exp/Cntr(USF)=0,0
Exp/Cntr=0.3,0.1

Type RM Length L Ch R = 1 ,12510   ,153.3,154.1,151.3
Node Name=D
XS GIS Cut Line= 2
2025277.25014885303131.3983687372025047.35633175 303051.55500711
#Sta/Elev= 30
       0 1804.52    15.5 1801.88    36.3 1799.85    46.7 1798.11    71.1 1797.01
    82.5 1795.94    95.4 1796.13   119.7 1795.71   123.1 1795.26   126.6 1793.37
   134.1 1787.16     137 1786.16   140.5 1786.06   150.9 1787.66   155.6 1787.94
   162.5 1789.39   165.6 1789.42   170.2 1788.25   175.2 1787.36   177.9 1787.37
   185.7 1787.94   188.2 1788.53   192.6 1789.35   206.5 1790.03   223.9 1791.37
   227.3 1792.08   230.8 1793.49   234.3 1795.45   237.8 1798.27243.3642 1804.26
#Mann= 5 ,-1 , 0
       0     .05       0    95.4    .016       0   119.7     .05       0
   170.2    .045       0   188.2      .1       0
#Block Obstruct= 2 ,-1
    20.5   43.34 1821.37   46.84   64.15  1818.1
Bank Sta=170.2,188.2
XS Rating Curve= 0 ,0
Exp/Cntr(USF)=0,0
Exp/Cntr=0.3,0.1

Type RM Length L Ch R = 1 ,12355   ,166.9,165.3,164
XS GIS Cut Line= 2
2025317.17182966  302970.33503582025098.29089003302918.023867838
#Sta/Elev= 30
       0 1801.92    25.7  1798.3    29.1  1797.1    39.2  1792.9      46 1790.55
    49.3 1789.74    65.6 1789.01    73.8  1789.9    79.7 1789.97    92.8 1789.49
    99.9 1788.86   106.7 1787.41   123.5 1785.63   130.3 1783.54     137 1780.58
   139.1 1780.05   143.8 1779.14   147.2 1778.98   153.9 1779.19   160.3 1780.33
   167.4 1782.17   174.1 1783.59   177.5 1783.85   184.3 1783.65   187.6 1783.82
     191 1784.79   194.4 1786.61     218 1801.33   221.4 1802.65225.0452 1803.56
#Mann= 5 ,-1 , 0
       0     .05       0    73.8    .016       0    92.8     .05       0
   139.1    .045       0   160.3      .1       0
Bank Sta=139.1,160.3
XS Rating Curve= 0 ,0
Exp/Cntr(USF)=0,0
Exp/Cntr=0.3,0.1

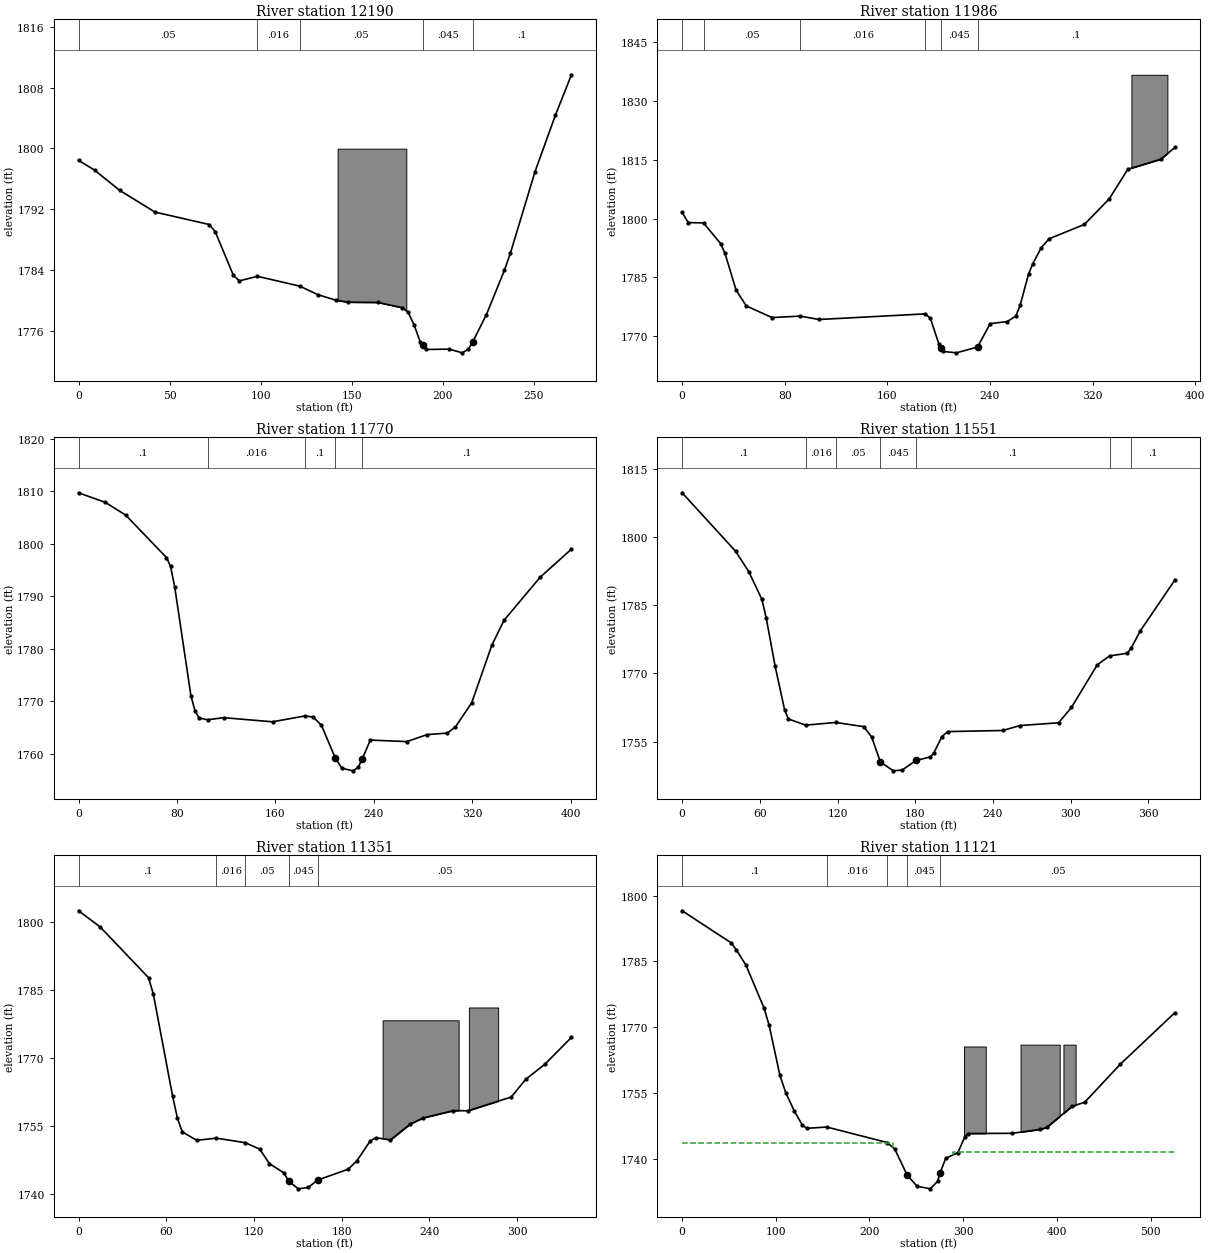
Type RM Length L Ch R = 1 ,12190   ,202.9,203.9,204.9
XS GIS Cut Line= 2
2025392.88536224302798.2588253972025124.44647401302762.466973633
#Sta/Elev= 30
       0 1798.42     8.9 1797.11    22.6 1794.46      42  1791.6    71.8 1789.96
    75.1 1789.03    85.1 1783.26    88.4 1782.54    98.3 1783.14   121.5 1781.85
   131.4 1780.73   141.3    1780     148 1779.73   164.5  1779.7   177.8 1779.01
   181.1  1778.4   184.4 1776.72   187.7 1774.52     189  1774.1     191  1773.5
   203.6 1773.55   210.9 1773.06   214.2 1773.56   216.5 1774.46   224.1 1778.09
     234 1783.94   237.3  1786.2   250.8 1796.92     262 1804.36270.8145 1809.68
#Mann= 5 ,-1 , 0
       0     .05       0    98.3    .016       0   121.5     .05       0
     189    .045       0   216.5      .1       0
#Block Obstruct= 1 ,-1
  142.34   180.1 1799.95
Bank Sta=189,216.5
XS Rating Curve= 0 ,0
Exp/Cntr(USF)=0,0
Exp/Cntr=0.3,0.1

Type RM Length L Ch R = 1 ,11986   ,216.7,216,215.6
XS GIS Cut Line= 3
2025413.53450749302606.9100794292025167.12137419302561.481959882
 2025034.9668446302540.832814634
#Sta/Elev= 30
       0 1801.58     4.8 1799.01    16.7 1798.92      30 1793.64    33.4 1791.19
    42.1 1781.76      50 1777.74    70.1 1774.76    92.1 1775.14   106.7 1774.27
   189.4  1775.7   193.5 1774.64   200.2 1767.99     202 1766.96   203.5 1766.12
   213.9 1765.76   230.3 1767.24   240.2 1773.21   253.5 1773.74   260.2 1775.15
   263.5 1777.85   270.1 1785.88   273.4 1788.51   280.1 1792.64   286.1 1794.87
   313.7 1798.54   333.1  1805.1   347.5 1812.62   373.1 1815.17384.3237 1818.21
#Mann= 6 ,-1 , 0
       0    .016       0    16.7     .05       0    92.1    .016       0
   189.4     .05       0     202    .045       0   230.3      .1       0
#Block Obstruct= 1 ,-1
  350.29  378.35 1836.73
Bank Sta=202,230.3
XS Rating Curve= 0 ,0
Exp/Cntr(USF)=0,0
Exp/Cntr=0.3,0.1

Type RM Length L Ch R = 1 ,11770   ,219.5,219.4,220
XS GIS Cut Line= 3
2025454.83279798302386.6525301132025202.91322595302350.860678349
2025056.99259953302341.224410566
#Sta/Elev= 30
       0 1809.71    21.8 1807.88    38.4 1805.45    71.5 1797.37    74.8 1795.69
    78.2 1791.79    91.4 1771.03    94.7 1768.17      98 1766.84   104.9 1766.47
   117.9 1766.88   157.7 1766.09   184.2 1767.21   190.8    1767   197.5 1765.41
   208.7  1759.2     214 1757.26   223.1 1756.75   227.3 1757.41   230.6 1758.98
   237.2 1762.61   266.9 1762.32   283.4 1763.65   299.8 1763.94   306.4 1765.13
   319.6  1769.7     336 1780.69   345.9 1785.43   375.4 1793.66400.6879 1798.98
#Mann= 5 ,-1 , 0
       0      .1       0   104.9    .016       0   184.2      .1       0
   208.7    .045       0   230.6      .1       0
Bank Sta=208.7,230.6
XS Rating Curve= 0 ,0
Exp/Cntr(USF)=0,0
Exp/Cntr=0.3,0.1

Type RM Length L Ch R = 1 ,11551   ,201.2,199.4,196.2
XS GIS Cut Line= 3
 2025469.9755045302193.9271744612025249.71795518302137.486177449
2025098.29089003302114.083812834
#Sta/Elev= 30
       0 1809.73    41.3 1796.88    51.5 1792.37    61.6  1786.3      65 1782.11
    71.8 1771.62    79.1 1762.05      82    1760    95.5 1758.64   118.7 1759.23
   140.3  1758.3   146.3 1756.05   153.1 1750.52   163.2 1748.59     170 1748.78
   180.7 1750.88   191.5 1751.64   194.2 1752.44   200.5 1756.08     205 1757.22
   247.5 1757.46     261 1758.55   290.7 1759.16   300.6 1762.53   320.5 1771.88
     330 1773.86   343.8 1774.45   346.9 1775.68   353.7 1779.33380.5988 1790.62
#Mann= 7 ,-1 , 0
       0      .1       0    95.5    .016       0   118.7     .05       0
   153.1    .045       0   180.7      .1       0     330    .016       0
   346.9      .1       0
Bank Sta=153.1,180.7
XS Rating Curve= 0 ,0
Exp/Cntr(USF)=0,0
Exp/Cntr=0.3,0.1

Type RM Length L Ch R = 1 ,11351   ,209.3,230,243
XS GIS Cut Line= 3
2025474.10533355301975.0462348282025182.26408071301936.501163698
2025139.58918053301933.747944332
#Sta/Elev= 30
       0 1802.38    14.8 1798.83    47.9 1787.65    51.2 1784.01    64.4 1761.51
    67.7 1756.66      71 1753.68    80.9 1751.84    94.2 1752.32     114 1751.33
     124 1749.88   130.6  1746.7   140.5 1744.67   143.8 1742.83   150.4 1741.16
   157.1 1741.47   163.7 1743.11   184.4 1745.47   190.2 1747.25   199.6 1751.73
   203.4 1752.43   213.3 1751.93   226.7 1755.38   235.5 1756.75   256.3 1758.38
   266.3 1758.35     296 1761.38   305.9 1765.28   319.1 1768.63337.1393 1774.51
#Mann= 5 ,-1 , 0
       0      .1       0    94.2    .016       0     114     .05       0
   143.8    .045       0   163.7     .05       0
#Block Obstruct= 2 ,-1
     208     260 1778.26     267     287 1781.09
Bank Sta=143.8,163.7
XS Rating Curve= 0 ,0
Exp/Cntr(USF)=0,0
Exp/Cntr=0.5,0.3

Type RM Length L Ch R = 1 ,11121   ,99.8,92.1,89.1
XS GIS Cut Line= 6
2025458.43786098301950.7741741552025419.41097646301866.030082056
2025349.16258432301752.2945900282025314.59591518301706.577382448
2025238.77225383301675.3558748332025083.77976959301636.328990313
#Sta/Elev= 30
       0 1796.53    52.4 1789.21    57.9 1787.61    68.1 1784.16    87.5 1774.31
    92.9 1770.39   104.4 1758.96   110.7 1754.98   119.8 1750.81   128.3 1747.65
     133  1746.9   154.5 1747.19   218.8 1743.66     227 1742.15   240.2 1736.22
   250.8 1733.69   264.9 1733.09   272.6 1734.81   275.2 1736.62   281.3 1740.06
   294.4 1741.35   301.5 1744.86     305 1745.71   352.4 1745.76   382.3 1746.66
   389.1  1747.1   416.1 1751.89   429.7 1752.85   467.6  1761.5526.1244 1773.32
#Mann= 5 ,-1 , 0
       0      .1       0   154.5    .016       0   218.8     .05       0
   240.2    .045       0   275.2     .05       0
#XS Ineff= 2 , 0
             225 1743.59     289         1741.57
Permanent Ineff=
       F       F
#Block Obstruct= 3 ,-1
  300.84   324.1 1765.57  361.25     403 1765.99     407     420 1765.99
Bank Sta=240.2,275.2
XS Rating Curve= 0 ,0
Exp/Cntr(USF)=0,0
Exp/Cntr=0.5,0.3

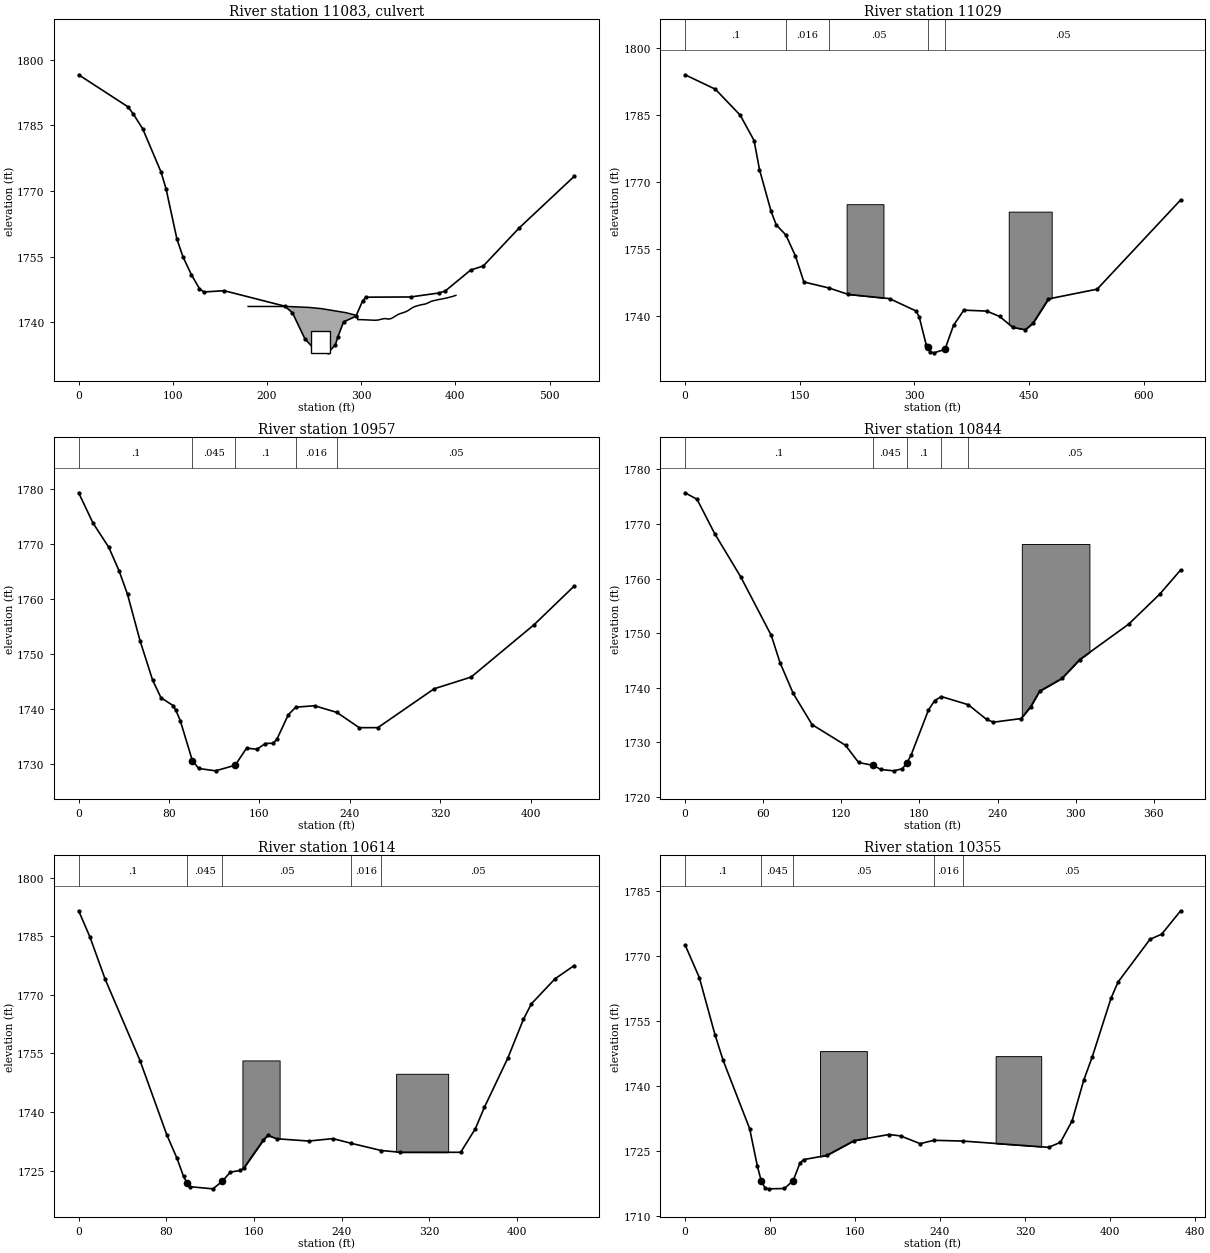
Type RM Length L Ch R = 2 ,11083   ,,,
BEGIN DESCRIPTION:
Elton Lawn Road
Survey ID: MIC010
END DESCRIPTION:
Bridge Culvert--1,0,-1,-1, 0
Deck Dist Width WeirC Skew NumUp NumDn MinLoCord MaxHiCord MaxSubmerge Is_Ogee
16,50,2.6,0, 156, 6, , , 0.98, 0, 0,0,,
     180     222     245     258     284     296 296.279 296.279 296.513 296.816
 296.816 298.852  299.51  299.51 300.291 300.291 301.316 303.805 303.805 303.829
 303.839 303.839 303.863 306.342 307.387 307.387 308.856 309.895 310.935 310.935
 311.369 312.422 312.422 313.882 314.483 314.483 315.926 316.395 318.031 318.031
 318.909 321.039 321.039 321.422  321.58  321.58 321.958 323.935 325.128 325.128
 326.448  327.99 328.676 328.676 328.961 329.655 329.655 331.475 332.224 332.224
 333.988 334.022 335.772 335.772 336.501 338.272 338.272 339.014  339.32  339.32
 340.053 341.528 342.868 342.868 344.041 346.085 346.416 346.416 346.554 346.889
 346.889 349.067 349.964 349.964  351.58 352.117 353.512 353.512 354.094 355.506
 355.506 356.607  357.06  357.06 358.149  359.12 360.608 360.608 361.633 364.123
 364.123 364.147 364.156 364.156  364.18  366.66 367.705 367.705 369.173 370.212
 371.253 371.253 371.686 372.739 372.739 374.199 374.801 374.801 376.244 376.713
 378.349 378.349 379.226 381.356 381.356  381.51  381.51 381.747 381.887 381.887
 382.164 384.345 384.458 384.458 385.323 385.323 386.968 387.043 388.706 388.706
 389.746  391.49  392.09  392.09 392.448 393.872 393.872 395.151 395.473 395.473
 396.012 397.854 398.856 398.856 400.533 400.556
1743.5861743.5861743.3651743.0891742.1611741.4951740.5721740.5721740.5821740.586
1740.5861740.585 1740.58 1740.581740.5681740.5681740.5671740.5321740.5321740.531
1740.5311740.5311740.5311740.5181740.5131740.5131740.4921740.4781740.4631740.463
1740.4631740.4561740.4561740.4431740.4381740.4381740.4571740.464 1740.48 1740.48
 1740.551740.6541740.6541740.674 1740.68 1740.681740.6941740.801 1740.82 1740.82
1740.7961740.7291740.7061740.7061740.7131740.7251740.725 1740.82 1740.86 1740.86
1741.0761741.0811741.3091741.3091741.4071741.6561741.6561741.7491741.7821741.782
1741.8421741.9651742.0691742.0691742.1441742.2751742.2971742.2971742.308 1742.34
 1742.341742.5611742.6741742.6741742.9071742.9911743.2021743.2021743.2691743.433
1743.4331743.541 1743.58 1743.581743.6491743.7131743.8021743.8021743.8641743.997
1743.9971743.9981743.9991743.999    17441744.0841744.1331744.1331744.2341744.338
1744.4281744.4281744.4671744.5761744.5761744.7331744.7981744.7981744.8761744.902
1744.9911744.9911745.0271745.1281745.1281745.1351745.1351745.1461745.1531745.153
1745.1641745.2491745.2541745.254 1745.29 1745.291745.3581745.361 1745.43 1745.43
1745.4831745.5721745.6021745.6021745.6191745.6931745.6931745.7621745.7811745.781
1745.8161745.935    1746    17461746.1241746.126
                                                                                
                                                                                
                                                                                
                                                                                
                                                                                
                                                                                
                                                                                
                                                                                
                                                                                
                                                                                
                                                                                
                                                                                
                                                                                
                                                                                
                                                                                
                                                
     180     259     291     334     355     382
1743.5861743.5861743.3651743.0891742.1611741.495
                                                
BR Coef=-1 , 1 , 0 ,, 0 ,,,0.8,0,1.2,0,
WSPro=,,,, 1 ,,,, 0 ,,,, 0 ,,,,-1 ,-1 ,-1 , 0 , 0 , 0 , 0 , 0
Culvert=2,5,20,50,0.012,0.4,1,8,1,1732.993,257,1731.701,329,Culvert #1  , 0 ,15
     257     329
BC Culvert Barrel=1,Barrel1,0
Culvert Bottom n=0.012
BC Design=,, 0 ,, 0 ,,,,,,
BC Use User HTab Curves=0
BC User HTab FreeFlow(D)= 0

Type RM Length L Ch R = 1 ,11029   ,103.2,72,54.7
XS GIS Cut Line= 5
2025533.15387693301925.2682319372025426.10129952301695.426844014
 2025335.7819382301611.7978057582025189.70988472301578.346190456
2025068.16901578301572.770921239
#Sta/Elev= 30
       0 1794.09    39.6 1790.85    72.1 1785.02    90.2 1779.34    97.3 1772.83
   112.3 1763.54   119.2 1760.41   131.8 1758.14   144.2 1753.47   155.4 1747.59
     188 1746.25   213.3 1744.81   267.4 1743.86     302 1741.09   306.1 1739.83
   315.4 1733.48   317.9 1732.92   320.6 1731.89   325.4 1731.69   339.9 1732.46
   351.1 1737.86   364.6 1741.27   394.5 1741.06   411.4 1739.86   428.6 1737.41
     445 1736.88   455.1 1738.35   475.3 1743.79     539 1745.98   648.2    1766
#Mann= 5 ,-1 , 0
       0      .1       0   131.8    .016       0     188     .05       0
   317.9    .045       0   339.9     .05       0
#XS Ineff= 2 , 0
             303  1736.7     354         1735.85
Permanent Ineff=
       F       F
#Block Obstruct= 2 ,-1
  211.27  259.48 1765.05  423.33  479.52 1763.38
Bank Sta=317.9,339.9
XS Rating Curve= 0 ,0
Exp/Cntr(USF)=0,0
Exp/Cntr=0.5,0.3

Type RM Length L Ch R = 1 ,10957   ,117.1,113.5,113.8
XS GIS Cut Line= 5
2025504.29858737 301516.027636232025391.10660963301575.739759192
 2025330.2776606301588.7750190142025187.83123814301571.991967982
2025082.94457233301566.513375118
#Sta/Elev= 30
       0 1779.23    12.7 1773.75    26.7 1769.33    35.8 1765.08    43.3 1760.78
    54.4 1752.36    65.5 1745.23    72.9 1742.04    83.7 1740.61    86.1 1739.76
      90 1737.87   100.7 1730.62   106.3 1729.21   121.2 1728.78   138.6  1729.8
   148.7 1732.91   157.7 1732.69   165.4 1733.74   172.1 1733.79   175.5 1734.51
   185.6 1738.96   192.2 1740.33   208.8 1740.59   228.6 1739.38   248.4 1736.61
   264.9 1736.62   314.7 1743.67   347.4 1745.79   403.3 1755.32438.6477  1762.3
#Mann= 5 ,-1 , 0
       0      .1       0   100.7    .045       0   138.6      .1       0
   192.2    .016       0   228.6     .05       0
Bank Sta=100.7,138.6
XS Rating Curve= 0 ,0
Exp/Cntr(USF)=0,0
Exp/Cntr=0.3,0.1

Type RM Length L Ch R = 1 ,10844   ,234.3,230,217.7
XS GIS Cut Line= 3
2025452.07957862301471.2070907682025262.10744233301511.128771581
2025083.14818351301563.439939544
#Sta/Elev= 30
       0 1775.72     9.2 1774.52    22.7 1768.25    42.7 1760.33    66.2 1749.59
    72.9 1744.62      83 1738.99    97.5 1733.27   123.2 1729.48   133.2 1726.33
   144.6 1725.79   150.2 1725.06   160.1  1724.8   166.8 1725.18   170.1 1726.16
   173.5 1727.64   186.9 1735.94   191.7 1737.68   196.8  1738.4   217.5 1736.91
   231.5 1734.22   236.8 1733.71     258 1734.37   265.4 1736.55   272.2 1739.38
   289.3 1741.71     303 1745.17   340.6 1751.65   364.5 1757.15380.5695 1761.59
#Mann= 5 ,-1 , 0
       0      .1       0   144.6    .045       0   170.1      .1       0
   196.8    .016       0   217.5     .05       0
#Block Obstruct= 1 ,-1
  258.59  310.51 1766.34
Bank Sta=144.6,170.1
XS Rating Curve= 0 ,0
Exp/Cntr(USF)=0,0
Exp/Cntr=0.3,0.1

Type RM Length L Ch R = 1 ,10614   ,265.9,259,248.8
XS GIS Cut Line= 3
2025277.25014885301239.9366639862025132.70613211301352.818658011
2024937.22755709301537.284355563
#Sta/Elev= 30
       0  1791.5    10.2 1784.88    24.3 1773.92      56 1753.18    80.4 1734.21
    89.8 1728.13    95.7 1723.55    99.1 1721.75   101.8 1720.89   122.5 1720.35
     131 1722.24   138.4 1724.63   147.6 1725.06   150.6 1725.63   168.4 1732.78
   172.6 1734.04   180.9 1733.16   209.9 1732.58     232  1733.2   248.3 1732.03
   276.1 1730.16   293.5 1729.71   348.6  1729.7     362 1735.73   370.2 1741.18
   391.6 1753.79   405.9 1763.75   413.1 1767.68   434.6 1774.07452.1733 1777.49
#Mann= 5 ,-1 , 0
       0      .1       0    99.1    .045       0     131     .05       0
   248.3    .016       0   276.1     .05       0
#Block Obstruct= 2 ,-1
  149.45   183.4 1753.21   289.7  337.18 1749.79
Bank Sta=99.1,131
XS Rating Curve= 0 ,0
Exp/Cntr(USF)=0,0
Exp/Cntr=0.3,0.1

Type RM Length L Ch R = 1 ,10355   ,306.4,315.3,310.5
XS GIS Cut Line= 3
2025015.69430904301089.8862085142024941.35738614301244.066493036
2024809.20285655301508.375552215
#Sta/Elev= 30
       0 1772.65    13.4 1765.11    28.2 1751.88    35.8    1746    60.8 1730.21
    68.1 1721.51    71.7 1718.19    75.4 1716.48      79 1716.32    93.6  1716.4
   101.8 1718.23   108.1 1722.25   111.6 1723.07   133.3 1724.03   159.1 1727.45
   192.1 1728.87   203.1 1728.53   221.4 1726.75   234.2 1727.53   261.8 1727.35
   342.5 1725.91   353.5 1727.07   364.5 1732.04   375.5 1741.48   383.4 1746.77
   401.1 1760.34   407.8  1764.1   437.8 1773.95   448.8 1775.13466.6718 1780.54
#Mann= 5 ,-1 , 0
       0      .1       0    71.7    .045       0   101.8     .05       0
   234.2    .016       0   261.8     .05       0
#Block Obstruct= 2 ,-1
  127.02  171.17 1748.13  292.46  335.38 1746.97
Bank Sta=71.7,101.8
XS Rating Curve= 0 ,0
Exp/Cntr(USF)=0,0
Exp/Cntr=0.3,0.1