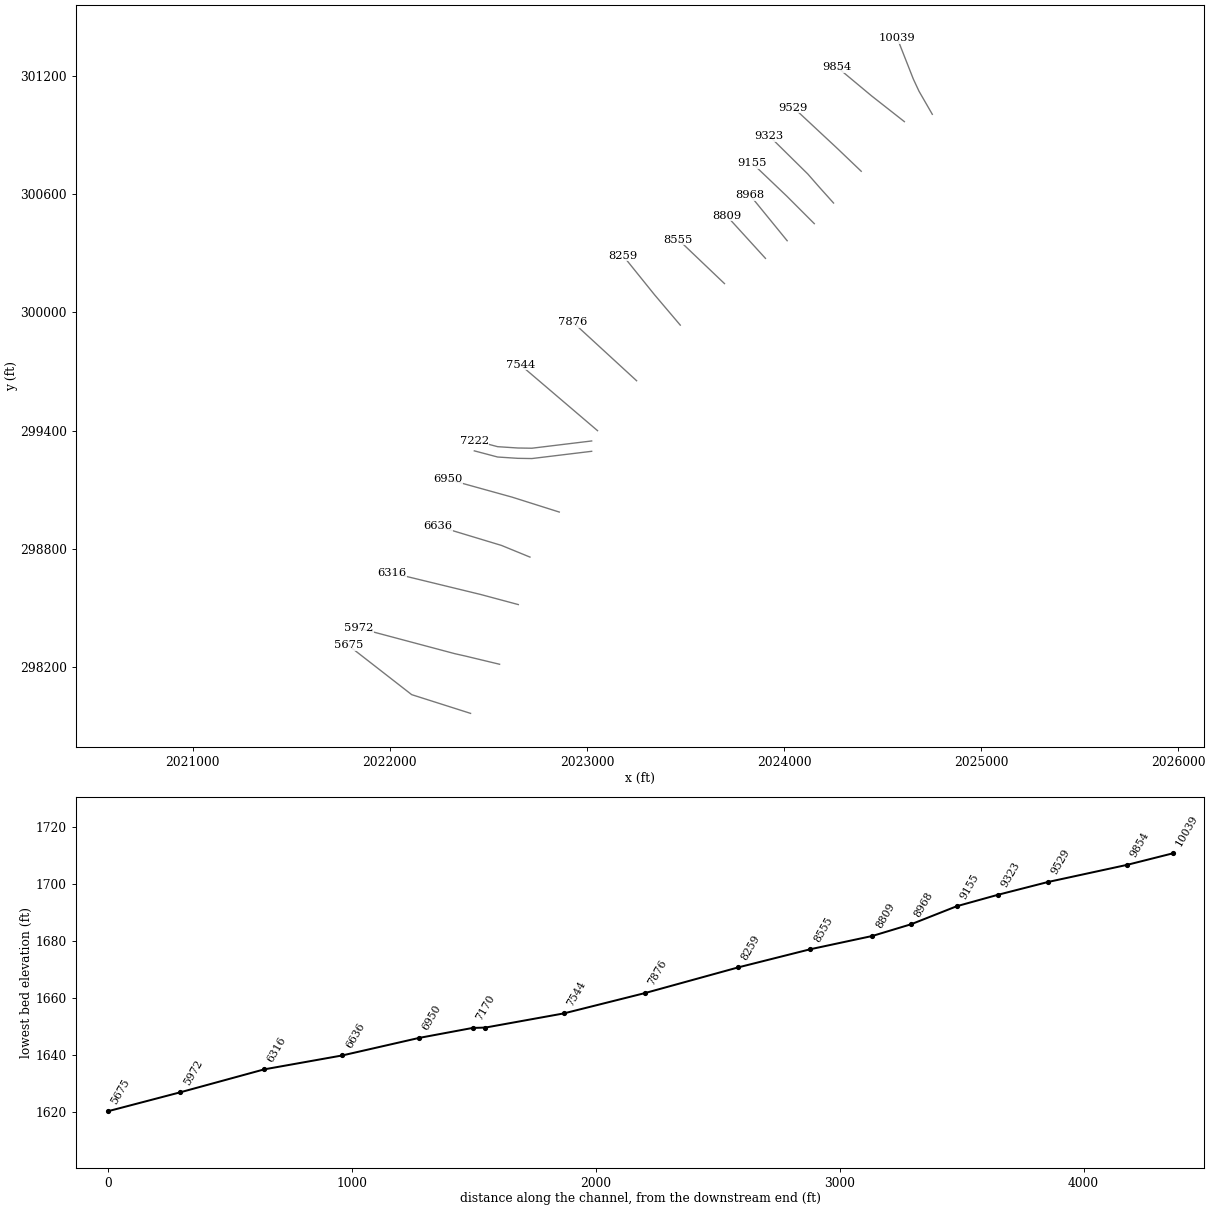
HEC-RAS study MILLCK.prj: MILLCK

--- MILLCK.g01 (geometry) --- (continued)

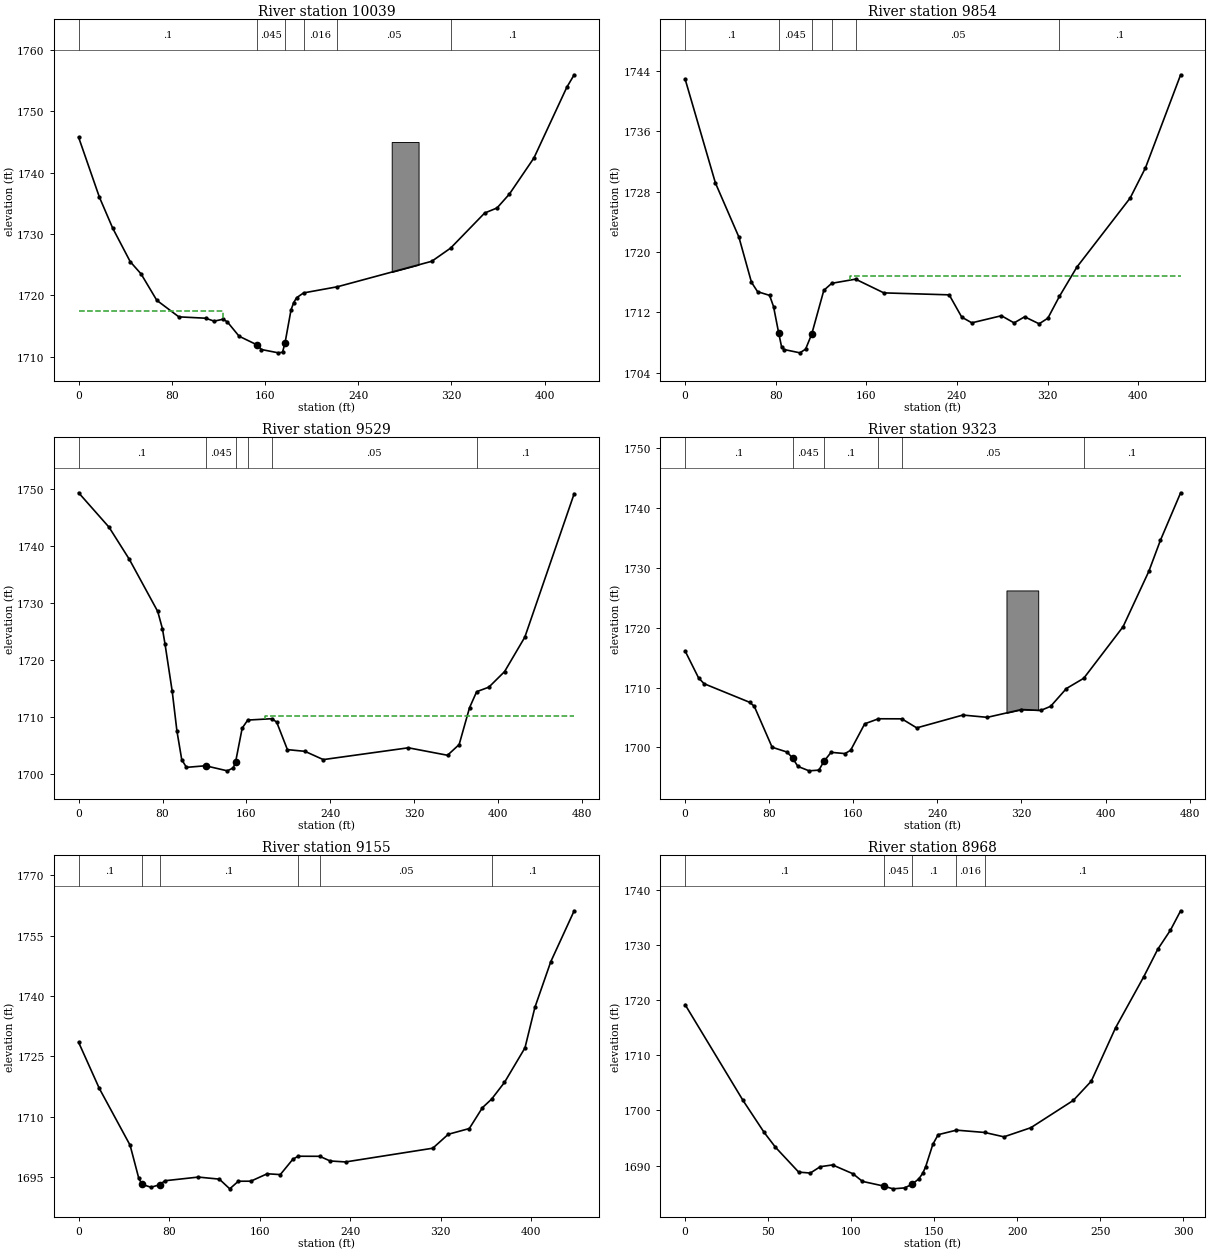
Type RM Length L Ch R = 1 ,10039   ,173,185.9,193.1
XS GIS Cut Line= 4
2024752.76185954301004.5364081542024685.30798506301121.548231229
2024656.39918171301183.495666974 2024575.1792104301389.987119458
#Sta/Elev= 30
       0 1745.73    17.8    1736    29.2 1730.96    44.3 1725.48    53.6 1723.49
    67.1 1719.19      86  1716.5     109 1716.28   116.3  1715.8   123.9 1716.11
   127.6 1715.69   137.7 1713.35   153.3 1711.92   156.9 1711.18   171.4 1710.64
     175 1710.74   177.2 1712.31   182.3 1717.64   184.6 1718.83   187.1 1719.62
   193.1  1720.4   222.1  1721.4   303.1 1725.55   319.3  1727.7   348.5 1733.41
   359.1 1734.23   369.7 1736.49   390.8 1742.38     419 1753.89425.3135 1755.92
#Mann= 6 ,-1 , 0
       0      .1       0   153.3    .045       0   177.2      .1       0
   193.1    .016       0   222.1     .05       0   319.3      .1       0
#XS Ineff= 2 , 0
          123.64  1717.5
Permanent Ineff=
       F       F
#Block Obstruct= 1 ,-1
  268.71  291.77 1744.97
Bank Sta=153.3,177.2
XS Rating Curve= 0 ,0
Exp/Cntr(USF)=0,0
Exp/Cntr=0.3,0.1

Type RM Length L Ch R = 1 ,9854    ,327,324.8,323.1
XS GIS Cut Line= 3
2024610.97106217300967.367946707 2024444.4012905301098.145866614
2024270.94847041301242.689883352
#Sta/Elev= 30
       0 1742.94    26.8 1729.14    47.5 1721.98    58.6 1715.99      64 1714.74
    74.6 1714.25    78.1 1712.76    82.7 1709.21    85.2 1707.42    87.4 1707.07
   101.4 1706.63   106.4 1707.12   111.8 1709.11   122.5 1714.92   129.5 1715.85
   150.5  1716.4   175.5 1714.58   233.2 1714.32   244.3 1711.36   253.2 1710.61
   279.3 1711.55   290.5  1710.6   299.8 1711.41   312.6 1710.48   320.3 1711.22
   330.5 1714.11   345.9 1717.99     393 1727.16   406.5 1731.16437.5593  1743.5
#Mann= 6 ,-1 , 0
       0      .1       0    82.7    .045       0   111.8      .1       0
   129.5    .016       0   150.5     .05       0   330.5      .1       0
#XS Ineff= 2 , 0
                          145.63         1716.76
Permanent Ineff=
       F       F
Bank Sta=82.7,111.8
XS Rating Curve= 0 ,0
Exp/Cntr(USF)=0,0
Exp/Cntr=0.3,0.1

Type RM Length L Ch R = 1 ,9529    ,210.2,206.1,205.6
XS GIS Cut Line= 3
2024392.09012253300715.4483746772024269.57186073300832.460197751
2024047.93770173301038.951650235
#Sta/Elev= 30
       0 1749.36      29 1743.32    48.4 1737.67    75.4 1728.55    79.9  1725.5
    82.3 1722.89    89.2 1714.55    93.7 1707.58    98.3 1702.55   102.8 1701.22
     121  1701.5   141.7 1700.61   147.3 1701.12   149.6 1702.16   155.9  1708.1
   161.2 1709.51   184.3 1709.75   188.8 1709.14     199 1704.33   215.7 1704.03
   233.2 1702.58   314.3 1704.65   351.6 1703.34   362.7 1705.22   372.6 1711.68
   379.4 1714.49     391 1715.28     406 1718.01   425.3 1724.05472.3379  1749.2
#Mann= 6 ,-1 , 0
       0      .1       0     121    .045       0   149.6      .1       0
   161.2    .016       0   184.3     .05       0   379.4      .1       0
#XS Ineff= 2 , 0
                          177.46         1710.18
Permanent Ineff=
       F       F
Bank Sta=121,149.6
XS Rating Curve= 0 ,0
Exp/Cntr(USF)=0,0
Exp/Cntr=0.3,0.1

Type RM Length L Ch R = 1 ,9323    ,153.1,168,151.7
Node Name=C
XS GIS Cut Line= 4
2024251.67593485 300554.385041742024178.71562163 300635.60501305
2024120.89801494300701.6822778452023925.41943992300894.407633496
#Sta/Elev= 30
       0 1716.11    12.8 1711.62    18.1 1710.64    61.4 1707.54    65.8 1706.88
    82.8 1700.04    97.1 1699.23   102.4  1698.2   107.3 1696.84     118  1696.1
   127.3 1696.22   132.2 1697.71   138.9 1699.19   152.1 1698.98   157.5 1699.53
   170.9 1703.95     184 1704.79   206.2 1704.78   220.4 1703.27   264.3 1705.41
   287.5 1705.03     320 1706.33   338.5 1706.19   347.8 1706.87   362.8 1709.84
   379.3 1711.55   416.7 1720.15   441.2 1729.39   452.2 1734.56471.4882 1742.51
#Mann= 6 ,-1 , 0
       0      .1       0   102.4    .045       0   132.2      .1       0
     184    .016       0   206.2     .05       0   379.3      .1       0
#Block Obstruct= 1 ,-1
  305.77  335.98 1726.21
Bank Sta=102.4,132.2
XS Rating Curve= 0 ,0
Exp/Cntr(USF)=0,0
Exp/Cntr=0.3,0.1

Type RM Length L Ch R = 1 ,9155    ,163.5,186.6,145.4
XS GIS Cut Line= 3
2024153.93664734300449.7627058152024014.89906933 300588.80028382
2023840.06963956300755.370055491
#Sta/Elev= 30
       0 1728.49    18.3 1717.04    45.5 1702.94    53.1 1694.81      56 1693.23
      64  1692.5    71.6 1693.13    76.3 1694.12   105.8 1695.03   124.4 1694.52
   133.6 1692.11   141.2    1694   152.2 1694.01   166.7 1695.85   178.3 1695.65
   189.3 1699.43     194 1700.21   213.1 1700.19   222.4 1699.03     236 1698.79
   313.1  1702.2   326.8 1705.66   345.4 1707.09     357 1712.27   365.1 1714.39
   376.5 1718.55   394.6 1727.12   403.4  1737.2   417.4 1748.51438.1052 1761.17
#Mann= 6 ,-1 , 0
       0      .1       0      56    .045       0    71.6      .1       0
     194    .016       0   213.1     .05       0   365.1      .1       0
Bank Sta=56,71.6
XS Rating Curve= 0 ,0
Exp/Cntr(USF)=0,0
Exp/Cntr=0.3,0.1

Type RM Length L Ch R = 1 ,8968    ,151.7,159.2,154.8
XS GIS Cut Line= 2
2024016.27567901300363.0362957712023827.68015241300594.306722553
#Sta/Elev= 30
       0 1719.16    34.9  1701.8    47.6 1696.02    54.4 1693.34    68.4 1688.83
    75.4 1688.66    81.4 1689.81    88.8 1690.13   101.1 1688.53   106.8 1687.15
   119.5 1686.31   125.2  1685.8   132.2 1685.97   136.5  1686.6   140.7 1687.59
   143.1 1688.61   144.9 1689.83   149.2 1693.87   152.4 1695.61   163.4 1696.43
   180.4 1696.01     192 1695.22   208.2 1696.87   233.8 1701.82   244.6  1705.3
   259.2 1714.95   276.2 1724.21   284.6 1729.17   292.3 1732.66298.4196 1736.16
#Mann= 5 ,-1 , 0
       0      .1       0   119.5    .045       0   136.5      .1       0
   163.4    .016       0   180.4      .1       0
Bank Sta=119.5,136.5
XS Rating Curve= 0 ,0
Exp/Cntr(USF)=0,0
Exp/Cntr=0.3,0.1

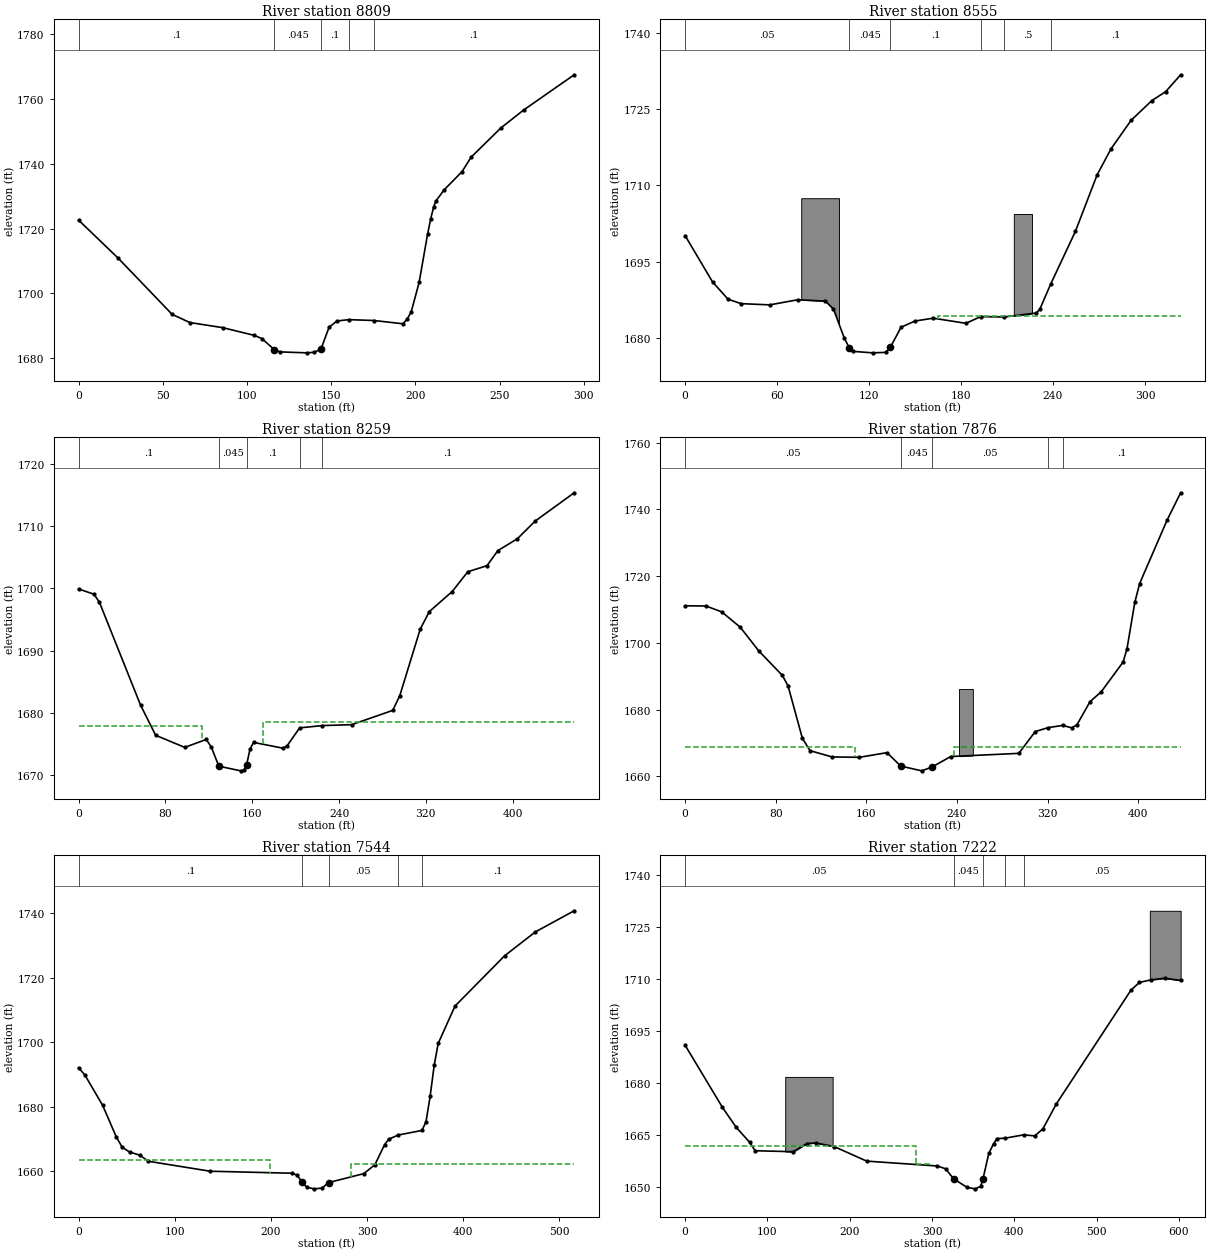
Type RM Length L Ch R = 1 ,8809    ,252.1,254,254.1
XS GIS Cut Line= 2
2023906.14690436300273.5566663622023707.91510997300491.060996311
#Sta/Elev= 30
       0 1722.63    23.4 1710.95    55.5 1693.57      66 1691.04    85.5 1689.46
   104.4 1687.06   108.8 1686.09   116.2 1682.67   119.5 1681.97   135.4 1681.68
   139.9 1681.85   143.9  1682.8   148.7 1689.55   153.4 1691.51   160.4 1691.93
   175.4 1691.66   192.6 1690.65   195.2 1692.17   197.5 1694.31   202.2 1703.41
   207.2 1718.22   209.1 1723.13   210.9 1726.84   212.1 1728.51     217 1731.96
   227.7 1737.63   233.1 1742.09   250.8 1751.12   264.2 1756.61294.2856 1767.52
#Mann= 5 ,-1 , 0
       0      .1       0   116.2    .045       0   143.9      .1       0
   160.4    .016       0   175.4      .1       0
Bank Sta=116.2,143.9
XS Rating Curve= 0 ,0
Exp/Cntr(USF)=0,0
Exp/Cntr=0.3,0.1

Type RM Length L Ch R = 1 ,8555    ,298,295.8,293.7
XS GIS Cut Line= 2
2023698.27884219300145.5319658222023464.25519604300368.542734504
#Sta/Elev= 30
       0  1700.1    17.9 1690.99      28 1687.59    36.5 1686.71    55.2 1686.47
    73.6 1687.48    91.5 1687.22    96.8 1685.62   103.8 1679.98   107.2 1677.95
   109.6 1677.32   122.3 1677.03   130.9 1677.12   133.9 1678.13   140.9 1682.07
     150 1683.29   161.8 1683.85   183.2 1682.84   192.8 1684.15   208.2 1684.09
   229.1 1684.87   231.4 1685.61   238.4  1690.5   254.6 1700.92   268.8 1712.07
   277.8 1717.15   290.9 1722.77   304.5 1726.68   313.5 1728.42323.2659 1731.75
#Mann= 6 ,-1 , 0
       0     .05       0   107.2    .045       0   133.9      .1       0
   192.8    .016       0   208.2      .5       0   238.4      .1       0
#XS Ineff= 2 , 0
                          164.85         1684.33
Permanent Ineff=
       F       F
#Block Obstruct= 2 ,-1
   75.74  100.41 1707.46  214.43  226.32 1704.35
Bank Sta=107.2,133.9
XS Rating Curve= 0 ,0
Exp/Cntr(USF)=0,0
Exp/Cntr=0.3,0.1

Type RM Length L Ch R = 1 ,8259    ,378,383.2,382
XS GIS Cut Line= 3
2023473.89146382299934.9106842882023343.11354392 300089.09096881
2023183.42682066300287.322763194
#Sta/Elev= 30
       0 1699.91    14.2 1699.06    19.2 1697.76    57.1 1681.22      71 1676.38
    97.8 1674.43   117.6 1675.71   122.3 1674.48   129.2 1671.41   149.4 1670.66
   152.5 1670.77   154.8 1671.62     158 1674.18   161.3 1675.23   188.1 1674.31
   192.1 1674.68   203.7 1677.57   224.7 1677.94   251.6 1678.08   289.5 1680.38
     296 1682.75   314.8 1693.43   323.2 1696.27   344.3  1699.5   358.7 1702.68
   376.4 1703.66   386.4 1706.08   404.4 1707.99   420.7 1710.82456.7242 1715.38
#Mann= 5 ,-1 , 0
       0      .1       0   129.2    .045       0   154.8      .1       0
   203.7    .016       0   224.7      .1       0
#XS Ineff= 2 , 0
           113.8 1677.85  169.58         1678.54
Permanent Ineff=
       F       F
Bank Sta=129.2,154.8
XS Rating Curve= 0 ,0
Exp/Cntr(USF)=0,0
Exp/Cntr=0.3,0.1

Type RM Length L Ch R = 1 ,7876    ,330.3,332,332.2
XS GIS Cut Line= 2
2023252.25730482299652.7056992272022930.13063895299948.676781121
#Sta/Elev= 30
       0 1711.11    18.5 1711.04    32.3 1709.28    48.7 1704.68      65 1697.59
    85.9 1690.22    90.9 1687.08   103.5 1671.41   110.3 1667.68   129.7 1665.79
   153.9 1665.69   178.2 1667.08   190.4 1663.05   208.9 1661.63   218.2 1662.81
   234.5 1665.92   294.6 1666.87   309.1  1673.4   320.4 1674.58   333.4 1675.25
   341.3 1674.51   345.9 1675.42   357.5 1682.39   367.3  1685.3   386.7 1694.26
   390.1 1698.23     397 1712.12   401.2 1717.72   425.5 1736.79437.4522 1744.98
#Mann= 5 ,-1 , 0
       0     .05       0   190.4    .045       0   218.2     .05       0
   320.4    .016       0   333.4      .1       0
#XS Ineff= 2 , 0
             150 1668.79  237.75         1668.79
Permanent Ineff=
       F       F
#Block Obstruct= 1 ,-1
  241.77  254.02 1686.16
Bank Sta=190.4,218.2
XS Rating Curve= 0 ,0
Exp/Cntr(USF)=0,0
Exp/Cntr=0.3,0.1

Type RM Length L Ch R = 1 ,7544    ,300.9,321.7,332.9
XS GIS Cut Line= 2
2023054.02551044299399.4095175142022661.69175072299733.925670538
#Sta/Elev= 30
       0  1692.1     6.4 1689.89      25 1680.43      39 1670.74    45.3 1667.42
      53 1665.94    63.9 1664.93    72.5 1663.07   136.8 1659.98   222.2 1659.35
   227.3 1658.73   232.4 1656.62   237.4 1654.99     245 1654.51   253.1 1654.74
   260.1 1656.45   296.7 1659.23   308.2 1661.97   318.3  1668.2   322.6 1669.89
   332.3  1671.2   357.1 1672.63   361.4 1675.26   365.7 1683.18     370 1692.97
   374.1 1699.64   391.6 1711.24   443.3 1726.87   475.1 1734.24 515.584 1740.82
#Mann= 5 ,-1 , 0
       0      .1       0   232.4    .045       0   260.1     .05       0
   332.3    .016       0   357.1      .1       0
#XS Ineff= 2 , 0
          199.44 1663.37  283.61         1662.31
Permanent Ineff=
       F       F
Bank Sta=232.4,260.1
XS Rating Curve= 0 ,0
Exp/Cntr(USF)=0,0
Exp/Cntr=0.5,0.3

Type RM Length L Ch R = 1 ,7222    ,52.7,52.5,52.4
XS GIS Cut Line= 5
2023024.27532081299347.123449789 2022720.9806754299310.326672957
2022649.61722942  299311.44172682022547.03227583 299318.13204986
2022428.83656843299349.353557476
#Sta/Elev= 30
       0 1690.95    45.4 1673.01      62 1667.29    78.5 1662.94    85.1 1660.53
   131.4 1660.24   147.9  1662.6   158.8 1662.77   180.9 1661.74   220.6 1657.53
   306.5 1656.13   316.4 1655.32   326.2 1652.44   342.4 1649.97   352.5 1649.54
     359 1650.23   361.8 1652.38   368.9 1659.73   374.7 1662.54   378.7 1664.02
   388.6 1664.14   411.3 1665.11   424.7  1664.8   434.6 1666.82     451 1674.04
   541.7 1706.86   551.9 1709.04   565.6 1709.77   582.5 1710.26601.9435 1709.62
#Mann= 5 ,-1 , 0
       0     .05       0   326.2    .045       0   361.8     .05       0
   388.6    .016       0   411.3     .05       0
#XS Ineff= 3 ,-1
       0     280    1662     280     298  1656.7   386.5     500 1661.88
Permanent Ineff=
       F       F       F
#Block Obstruct= 2 ,-1
  121.61  179.21 1681.81   564.5  601.94  1729.7
Bank Sta=326.2,361.8
XS Rating Curve= 0 ,0
Exp/Cntr(USF)=0,0
Exp/Cntr=0.5,0.3

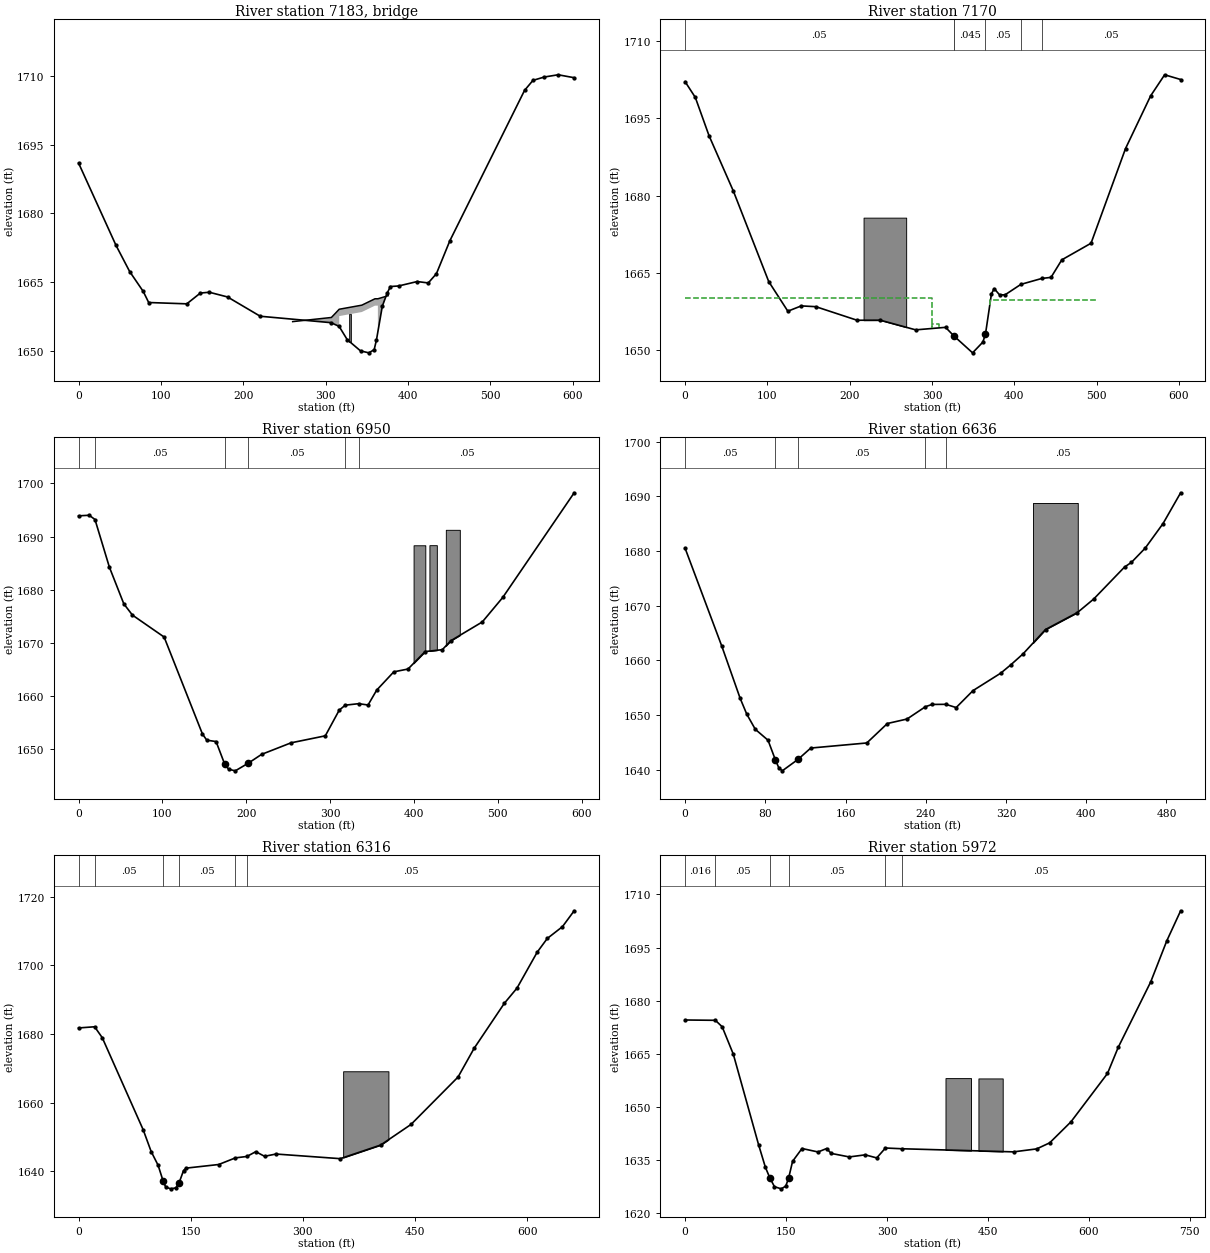
Type RM Length L Ch R = 3 ,7183    ,,,
BEGIN DESCRIPTION:
Private Driveway
Survey ID: LIC110
END DESCRIPTION:
Bridge Culvert--1,0,-1,-1, 0
Deck Dist Width WeirC Skew NumUp NumDn MinLoCord MaxHiCord MaxSubmerge Is_Ogee
23,12,2.6,0, 10, 10, , , 0.98, 0, 0,0,,
     260     307     312   316.5   316.5     344     360   363.5   363.5     376
1656.3551657.2631658.197 1659.06 1659.061659.9521661.3461661.3461661.3461662.017
                                 1657.561658.4521659.8461659.846
     260     307     312   316.5   316.5     344     360   363.5   363.5     376
1656.3551657.2631658.197 1659.06 1659.061659.9521661.3461661.3461661.3461662.017
                                 1657.561658.4521659.8461659.846
Pier Skew, UpSta & Num, DnSta & Num=  ,330, 2 ,330, 2 , 0 , 0 , 0 ,,
       2       2
       0    1659
       2       2
       0    1659
BR Coef=-1 , 1 , 0 ,1.25, 0 ,,,0.8,0,2,0,
WSPro=,,,, 1 ,,,, 0 ,,,, 0 ,,,,-1 ,-1 ,-1 , 0 , 0 , 0 , 0 , 0
BC Design=,, 0 ,, 0 ,,,,,,
BC Use User HTab Curves=0
BC User HTab FreeFlow(D)= 0

Type RM Length L Ch R = 1 ,7170    ,230.3,220,205.8
XS GIS Cut Line= 5
2023024.27532081299294.715919149 2022720.9806754299257.919142316
2022649.61722942 299259.034196162022547.03227583 299265.72451922
2022428.83656843299296.946026836
#Sta/Elev= 30
       0 1702.16    12.4  1699.1    29.1 1691.64    58.7 1680.85   101.6 1663.27
   124.8 1657.51   141.1 1658.54   158.8 1658.39   208.9 1655.75   237.1 1655.76
   280.1 1653.88   316.4 1654.37   326.2 1652.75   326.3 1652.73   349.2 1649.41
   361.7  1651.5   364.9 1653.08   372.1 1660.85   375.4 1661.91     382 1660.69
   388.6 1660.69   407.9 1662.73   433.3 1663.88   444.5 1664.09   457.6  1667.5
   493.1 1670.73     535 1689.15   565.5  1699.4   582.5  1703.5601.9435 1702.58
#Mann= 6 ,-1 , 0
       0     .05       0   326.2    .045       0   326.3    .045       0
   364.9     .05       0   407.9    .016       0   433.3     .05       0
#XS Ineff= 3 ,-1
       0     300    1660     300     309  1655.1 370.167     500 1659.77
Permanent Ineff=
       F       F       F
#Block Obstruct= 1 ,-1
  216.78  268.54 1675.71
Bank Sta=326.3,364.9
XS Rating Curve= 0 ,0
Exp/Cntr(USF)=0,0
Exp/Cntr=0.5,0.3

Type RM Length L Ch R = 1 ,6950    ,301.9,313.8,276.6
XS GIS Cut Line= 3
 2022859.9235451298986.4266125462022620.39346022299062.140145124
2022292.76035562299152.996384217
#Sta/Elev= 30
       0 1693.89    12.6    1694    19.5  1693.2    36.7 1684.23    53.9 1677.33
    64.2 1675.21     102 1671.08   147.7 1652.84   152.9 1651.67     164 1651.41
   174.3 1647.14     179  1646.2   186.9  1645.9   202.6 1647.36   218.3    1649
   253.4 1651.17   294.3 1652.49   310.9 1657.32   318.1 1658.26   334.1 1658.54
   345.3 1658.29   355.6 1661.09     376 1664.53     393 1665.06   413.4 1668.35
   433.9  1668.7   443.9 1670.37   481.6 1673.92     506 1678.53 591.209 1698.23
#Mann= 6 ,-1 , 0
       0    .016       0    19.5     .05       0   174.3    .045       0
   202.6     .05       0   318.1    .016       0   334.1     .05       0
#Block Obstruct= 3 ,-1
  399.61  413.61 1688.35  418.51  427.36 1688.37  438.09  454.77 1691.26
Bank Sta=174.3,202.6
XS Rating Curve= 0 ,0
Exp/Cntr(USF)=0,0
Exp/Cntr=0.3,0.1

Type RM Length L Ch R = 1 ,6636    ,307,320.4,300.2
XS GIS Cut Line= 3
2022711.24969932298757.9094051312022566.70568258 298817.10362151
2022243.20240702298914.842909019
#Sta/Elev= 30
       0  1680.5    36.7 1662.53    54.9 1653.04    61.5 1650.14      70 1647.37
    82.7 1645.37    90.1 1641.74    93.4 1640.35    96.9 1639.77   112.7 1641.88
   125.3 1643.94   181.2 1644.87   201.7 1648.43   221.3 1649.25   239.7 1651.51
   246.3 1651.92     260 1651.94   270.3 1651.35   287.1 1654.45   314.8 1657.65
   325.1 1659.22   337.1 1661.19   359.4 1665.63   391.2 1668.73   407.4  1671.2
   438.2 1677.06   445.1 1677.92   458.8 1680.52   476.6 1685.02494.1409 1690.65
#Mann= 5 ,-1 , 0
       0     .05       0    90.1    .045       0   112.7     .05       0
   239.7    .016       0     260     .05       0
#Block Obstruct= 1 ,-1
  346.88  391.57 1688.78
Bank Sta=90.1,112.7
XS Rating Curve= 0 ,0
Exp/Cntr(USF)=0,0
Exp/Cntr=0.3,0.1

Type RM Length L Ch R = 1 ,6316    ,343,343.5,345.8
Node Name=B
XS GIS Cut Line= 3
2022652.05548294298517.0027105662022462.08334665298567.937268846
2022009.17876087298678.066043504
#Sta/Elev= 30
       0 1681.75    21.4 1682.09    31.6 1678.91    86.3 1652.11      97 1645.75
   106.3 1641.75   113.1 1637.09   116.5 1635.38   123.3 1634.88   130.1 1635.17
   134.5 1636.72   140.3  1640.2   143.7 1640.91   187.4 1641.97   209.7  1643.9
     225 1644.31   236.9  1645.7   248.7 1644.36     264 1645.02   349.9 1643.67
     404 1647.64   444.5 1653.63   507.5 1667.46   528.9 1675.79   569.4 1688.93
   586.3 1693.35   613.3 1703.81   626.8 1707.81   647.1 1711.25662.7836 1715.88
#Mann= 6 ,-1 , 0
       0    .016       0    21.4     .05       0   113.1    .045       0
   134.5     .05       0   209.7    .016       0     225     .05       0
#Block Obstruct= 1 ,-1
  353.79  414.36 1669.13
Bank Sta=113.1,134.5
XS Rating Curve= 0 ,0
Exp/Cntr(USF)=0,0
Exp/Cntr=0.3,0.1

Type RM Length L Ch R = 1 ,5972    ,295.5,297.1,294.2
XS GIS Cut Line= 4
2022557.06941479298214.1485802572022384.99320439298255.446870754
2022329.92881706298267.8363579032021843.98559888298397.237668126
#Sta/Elev= 30
       0 1674.53      45 1674.44    55.1 1672.61    71.6 1664.89   109.1 1639.37
   119.3 1632.94     126  1629.9   132.8 1627.45   142.9 1626.85   149.6 1627.63
   153.9 1629.95   159.7 1634.62   173.7 1638.24   197.6 1637.26   210.2 1638.23
     217 1636.86   243.9 1635.86   267.7 1636.45   284.7 1635.58   297.7 1638.38
   322.1 1638.17     488 1637.29   522.4 1638.13   541.7 1639.84   573.3 1645.77
   627.6 1659.43   643.5 1666.79   691.8 1685.28   715.8 1696.93736.2809 1705.37
#Mann= 6 ,-1 , 0
       0    .016       0      45     .05       0     126    .045       0
   153.9     .05       0   297.7    .016       0   322.1     .05       0
#Block Obstruct= 2 ,-1
   386.9   424.8 1658.12  435.84  471.91 1658.03
Bank Sta=126,153.9
XS Rating Curve= 0 ,0
Exp/Cntr(USF)=0,0
Exp/Cntr=0.3,0.1

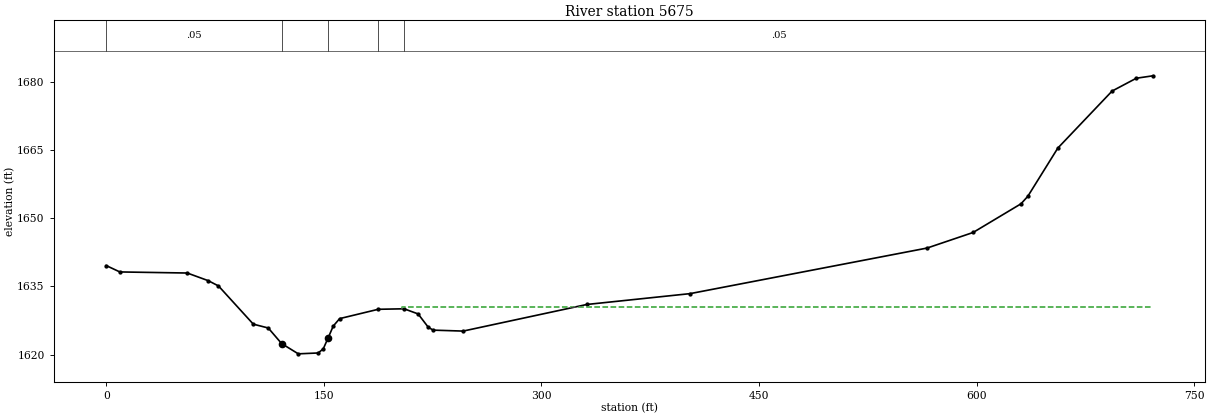
Type RM Length L Ch R = 1 ,5675    ,277.5,279.3,281.7
XS GIS Cut Line= 3
2022409.77217869297964.9822275932022111.04787743298059.968295736
2021788.92121156298310.511258083
#Sta/Elev= 30
       0 1639.59     9.4 1638.19    55.9 1637.95    70.4 1636.26    77.4 1635.11
   101.4 1626.71   111.7 1625.87   120.9 1622.45   132.4 1620.19   146.1 1620.38
   149.6 1621.28     153 1623.72   156.5  1626.3   160.9 1627.93   187.5 1629.98
   205.3 1630.09     215 1628.96   221.9 1626.07   225.3  1625.4     246 1625.19
   331.3 1631.04   402.4 1633.42   565.8 1643.44   597.5 1646.86   630.5 1653.16
   635.2  1654.8   655.9 1665.41   693.3 1677.94     710 1680.76721.5521  1681.3
#Mann= 5 ,-1 , 0
       0     .05       0   120.9    .045       0     153     .05       0
   187.5    .016       0   205.3     .05       0
#XS Ineff= 2 , 0
                          203.72         1630.55
Permanent Ineff=
       F       F
Bank Sta=120.9,153
XS Rating Curve= 0 ,0
Exp/Cntr(USF)=0,0
Exp/Cntr=0.3,0.1