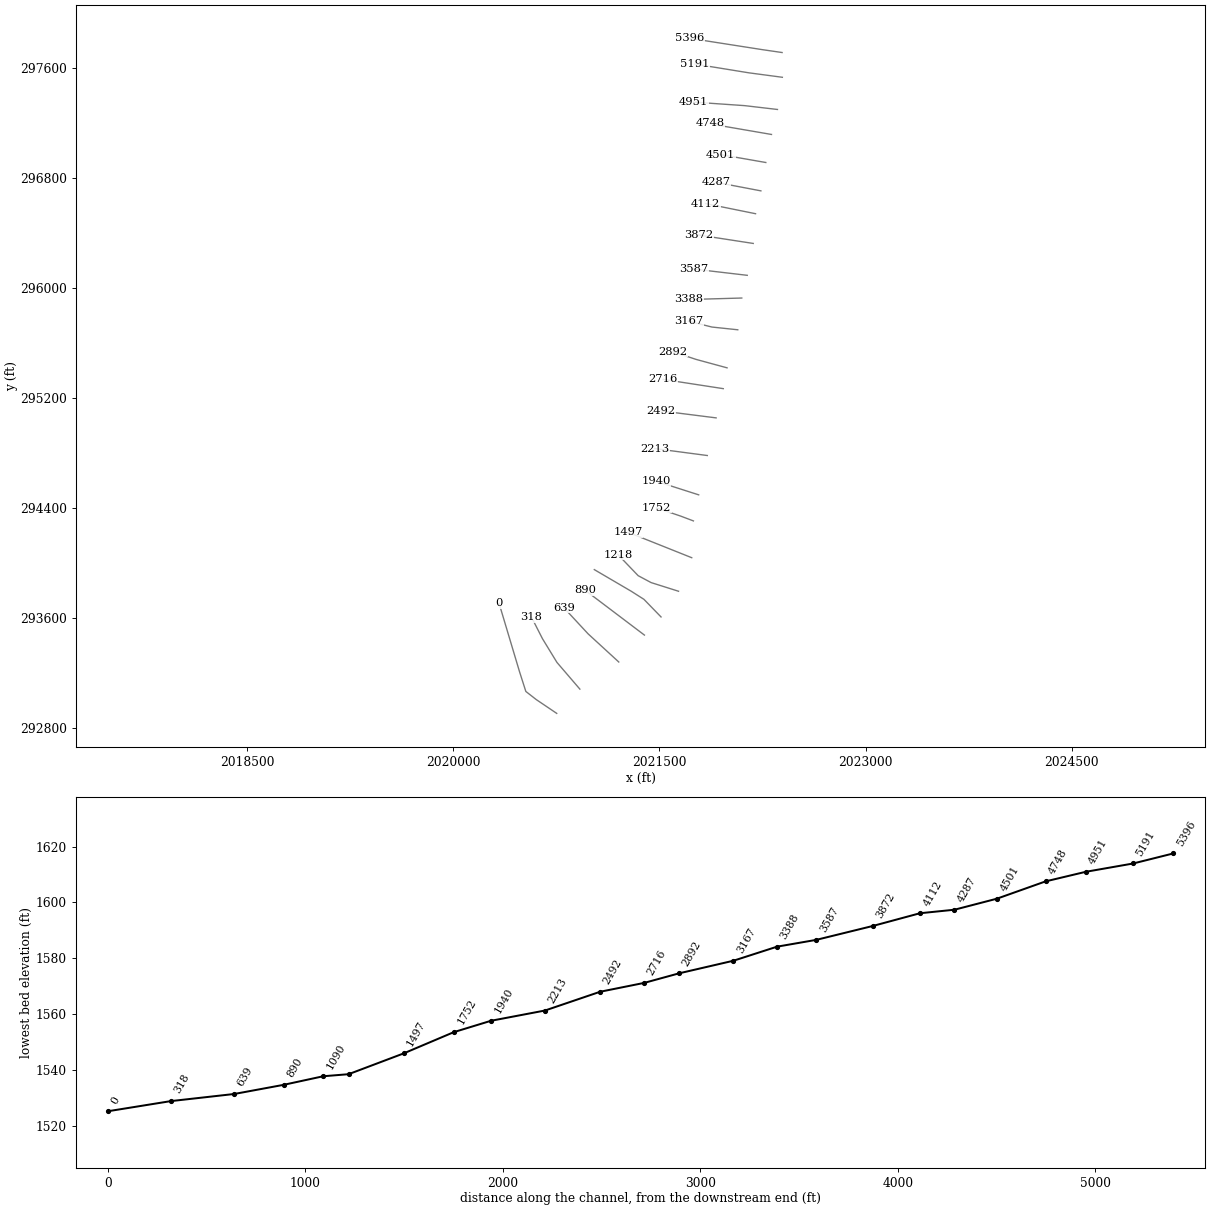
HEC-RAS study MILLCK.prj: MILLCK

--- MILLCK.g01 (geometry) --- (continued)

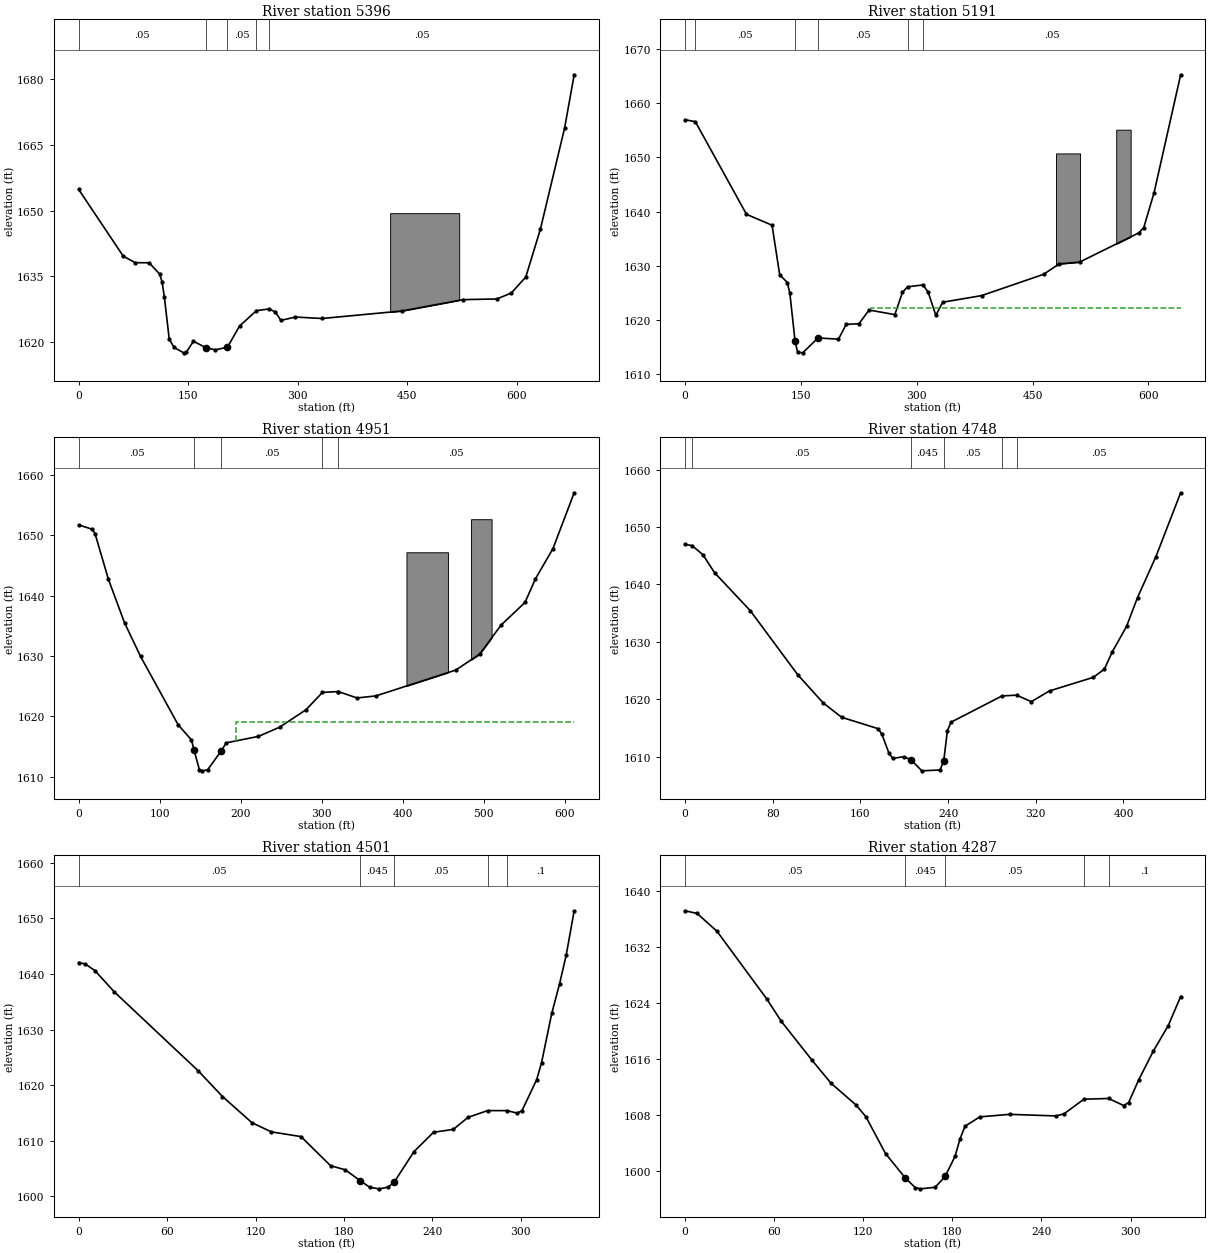
Type RM Length L Ch R = 1 ,5396    ,186.7,204.2,185.1
XS GIS Cut Line= 3
2022393.25286249297713.0626555632022251.46206512297733.711800811
2021722.84394676297816.308381805
#Sta/Elev= 30
       0 1654.86    61.1 1639.61    77.6 1638.13    96.6 1638.11   110.8 1635.54
   114.1 1633.83   117.4 1630.23     124 1620.69   130.7 1618.77   143.9 1617.55
   147.3  1617.7   157.2 1620.19   173.8 1618.76   187.1 1618.23   203.7 1618.83
   220.3 1623.67   243.4 1627.18   260.2 1627.56   269.2 1626.91   276.8 1624.95
   296.7 1625.72   333.2 1625.39   442.8 1627.11   525.8 1629.69   572.3 1629.85
   592.2 1631.19   612.1 1634.86   632.1 1645.79   665.3 1668.92678.3185 1681.02
#Mann= 5 ,-1 , 0
       0     .05       0   173.8    .045       0   203.7     .05       0
   243.4    .016       0   260.2     .05       0
#Block Obstruct= 1 ,-1
   426.4  520.93 1649.43
Bank Sta=173.8,203.7
XS Rating Curve= 0 ,0
Exp/Cntr(USF)=0,0
Exp/Cntr=0.3,0.1

Type RM Length L Ch R = 1 ,5191    ,239.3,240.3,240.2
XS GIS Cut Line= 3
2022395.21997398297533.0103903012022152.13823611 297565.34695176
2021760.75433708297628.905020834
#Sta/Elev= 30
       0 1656.96    13.3 1656.59    79.5  1639.5   112.6 1637.49   122.5 1628.35
   132.4 1626.91   135.7 1624.89   142.4  1616.1   145.7 1614.06   152.3 1613.94
   172.2 1616.69   198.6 1616.46   208.6 1619.19   225.1 1619.31   238.3 1621.84
   271.6 1620.99   281.5 1625.11   288.2 1626.13   308.1 1626.47   314.8 1625.13
   324.7 1620.85   333.6 1623.28   383.9  1624.5   464.3 1628.43   484.3 1630.35
   510.8 1630.68   588.1 1636.12     594 1637.06   607.3 1643.47641.7341 1665.25
#Mann= 6 ,-1 , 0
       0    .016       0    13.3     .05       0   142.4    .045       0
   172.2     .05       0   288.2    .016       0   308.1     .05       0
#XS Ineff= 2 , 0
                          240.17         1622.21
Permanent Ineff=
       F       F
#Block Obstruct= 2 ,-1
  480.35  511.38 1650.74   558.3  577.01 1655.12
Bank Sta=142.4,172.2
XS Rating Curve= 0 ,0
Exp/Cntr(USF)=0,0
Exp/Cntr=0.3,0.1

Type RM Length L Ch R = 1 ,4951    ,197.6,203.1,192.5
XS GIS Cut Line= 3
2022359.53825099297298.849083184 2022120.9167285 297326.72542927
2021750.71885249297352.371667668
#Sta/Elev= 30
       0 1651.72      17    1651    20.3 1650.25    36.8 1642.68    56.6 1635.51
    76.4 1629.92   122.7 1618.61   139.2 1616.08   142.5 1614.34   149.1 1611.09
   152.4 1610.96     159 1611.11   175.5 1614.18   175.5 1614.19   182.1  1615.6
   221.8 1616.67   248.2 1618.21   280.6  1621.1   300.8 1623.96   320.5  1624.1
   320.5 1624.09   343.5 1623.04   366.7 1623.38   465.2 1627.66   494.8 1630.31
   521.1 1635.11   550.7 1638.88   563.5 1642.77   585.1 1647.78611.3295 1657.05
#Mann= 5 ,-1 , 0
       0     .05       0   142.5    .045       0   175.5     .05       0
   300.8    .016       0   320.5     .05       0
#XS Ineff= 2 , 0
                          194.03         1619.11
Permanent Ineff=
       F       F
#Block Obstruct= 2 ,-1
  404.42  455.61 1647.19  484.11  509.46 1652.67
Bank Sta=142.5,175.5
XS Rating Curve= 0 ,0
Exp/Cntr(USF)=0,0
Exp/Cntr=0.3,0.1

Type RM Length L Ch R = 1 ,4748    ,226.2,246.8,209.9
XS GIS Cut Line= 3
 2022316.0511511297117.0953067082021965.92424427297177.308214253
2021871.14466758297197.379183434
#Sta/Elev= 30
       0 1646.97     6.3 1646.78    16.3 1645.17    26.9 1642.05    59.5 1635.43
   102.8 1624.27   126.1 1619.35   142.8 1616.87     176 1614.89   179.4 1613.99
     186 1610.62   189.4  1609.7   199.3    1610     206 1609.49     216 1607.54
   232.6 1607.69     236 1609.29   239.3  1614.5   242.6 1616.01   289.2 1620.59
   302.5 1620.72   315.9 1619.59   332.5 1621.46   372.6 1623.83   382.6 1625.27
   389.6  1628.2   402.8  1632.7   412.8 1637.72   429.6 1644.85452.1482 1655.97
#Mann= 6 ,-1 , 0
       0    .016       0     6.3     .05       0     206    .045       0
     236     .05       0   289.2    .016       0   302.5     .05       0
Bank Sta=206,236
XS Rating Curve= 0 ,0
Exp/Cntr(USF)=0,0
Exp/Cntr=0.3,0.1

Type RM Length L Ch R = 1 ,4501    ,213.8,214.6,212.8
XS GIS Cut Line= 2
2022274.79415889296913.040453364 2021943.6231674296971.023253221
#Sta/Elev= 30
       0 1642.05     4.4 1641.81      11 1640.62    24.3 1636.75      81 1622.61
    97.6 1617.95   117.6 1613.24   130.7 1611.59   150.9 1610.74   170.9 1605.51
   180.9 1604.76   190.9 1602.83   197.5 1601.62   203.9 1601.34     210 1601.64
   214.2 1602.59   227.5 1608.03   240.8 1611.52   254.2 1612.04   264.2  1614.2
   277.5 1615.42   290.8 1615.41   297.5 1614.96   300.8 1615.41   310.8 1620.99
   314.1 1624.07     321 1632.91   326.3 1638.22   330.8 1643.39336.2086 1651.37
#Mann= 5 ,-1 , 0
       0     .05       0   190.9    .045       0   214.2     .05       0
   277.5    .016       0   290.8      .1       0
Bank Sta=190.9,214.2
XS Rating Curve= 0 ,0
Exp/Cntr(USF)=0,0
Exp/Cntr=0.3,0.1

Type RM Length L Ch R = 1 ,4287    ,175.6,174.8,175.3
XS GIS Cut Line= 2
 2022239.1124359296706.7554923332021911.28660594296769.198507564
#Sta/Elev= 30
       0 1637.19     8.1 1636.81    21.5 1634.25    54.9  1624.6    64.8 1621.37
    85.6 1615.77    98.3 1612.51     115 1609.42   121.7 1607.74     135 1602.44
   148.4 1598.93   155.1 1597.56   158.4  1597.4   168.4 1597.62   175.1 1599.17
   181.8 1602.05   185.1 1604.52   188.5 1606.36   198.5  1607.7   218.5 1608.06
     250 1607.83   255.3 1608.15   268.6 1610.23   285.3 1610.33   295.3 1609.32
   298.7 1609.75   305.4 1612.96   315.4 1617.14   325.4 1620.77333.7198 1624.92
#Mann= 5 ,-1 , 0
       0     .05       0   148.4    .045       0   175.1     .05       0
   268.6    .016       0   285.3      .1       0
Bank Sta=148.4,175.1
XS Rating Curve= 0 ,0
Exp/Cntr(USF)=0,0
Exp/Cntr=0.3,0.1

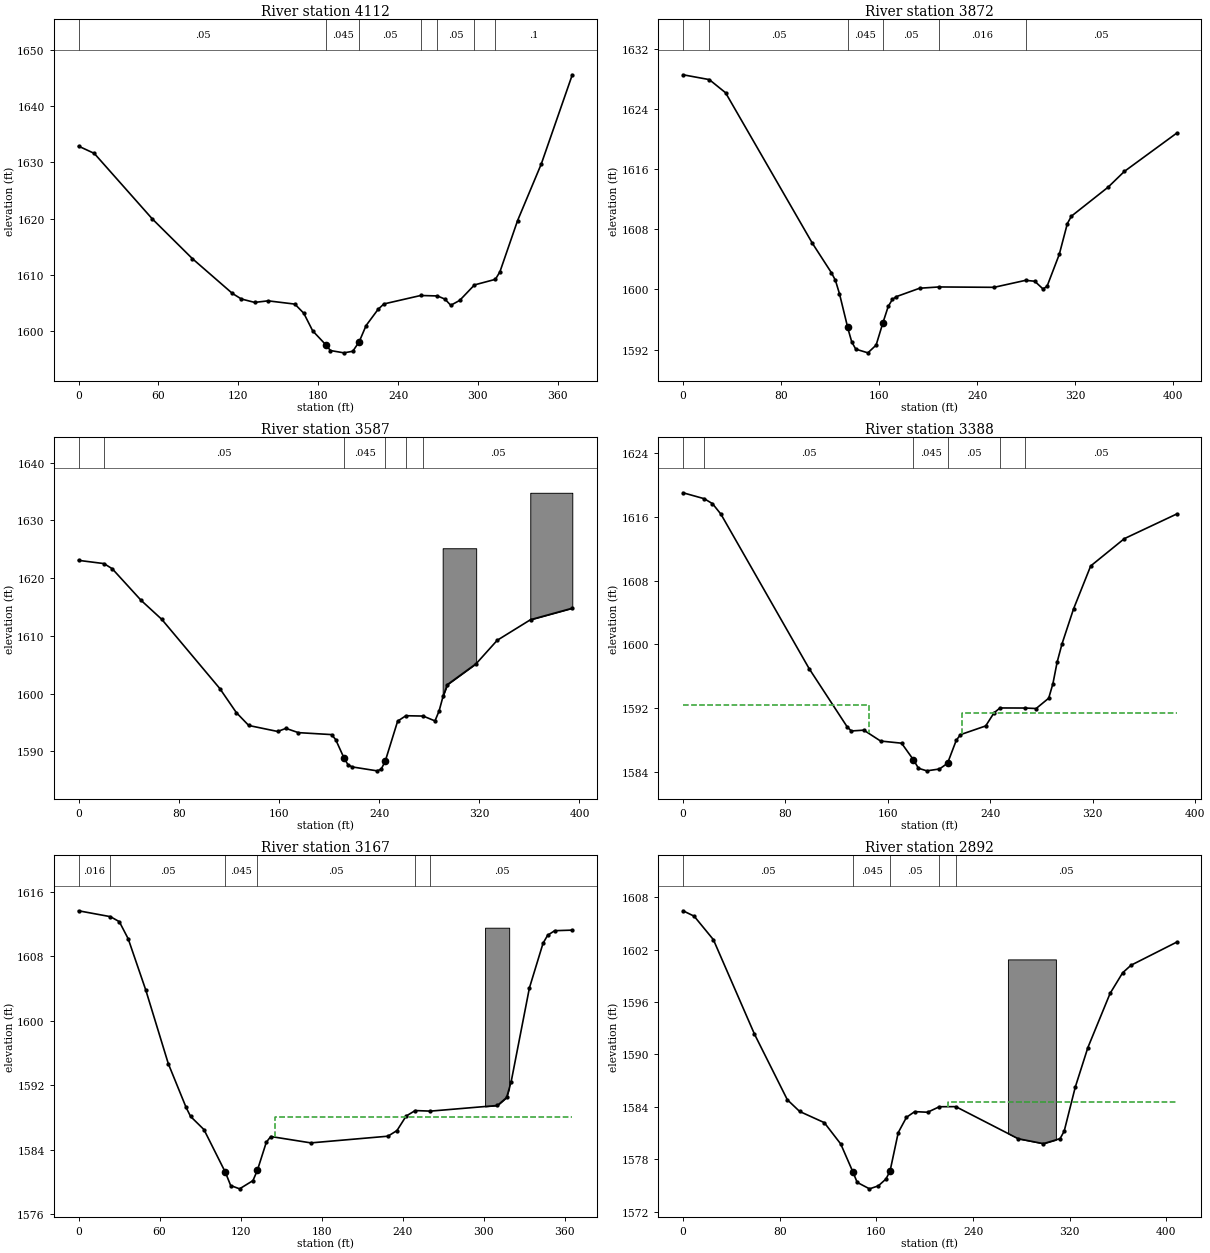
Type RM Length L Ch R = 1 ,4112    ,235.9,239.6,240.6
XS GIS Cut Line= 2
2022200.08555138296540.6124696642021836.57799843296614.206023329
#Sta/Elev= 30
       0 1632.87    11.8 1631.58    55.4 1619.94    85.5 1612.88   115.6 1606.69
   122.3 1605.71   132.3  1605.1   142.4 1605.38   162.5  1604.8   169.2 1603.17
   175.9 1600.04   186.1 1597.48   189.2 1596.55   199.3 1596.14     206 1596.42
   210.8 1598.11     216 1600.99   225.1  1603.9   229.4 1604.83     257 1606.33
   269.6 1606.25   275.2 1605.69   279.6 1604.59   286.3 1605.46   297.4 1608.21
   313.1  1609.2   316.5 1610.53   329.8 1619.65   347.6 1629.71370.8824 1645.55
#Mann= 7 ,-1 , 0
       0     .05       0   186.1    .045       0   210.8     .05       0
     257    .016       0   269.6     .05       0   297.4    .016       0
   313.1      .1       0
Bank Sta=186.1,210.8
XS Rating Curve= 0 ,0
Exp/Cntr(USF)=0,0
Exp/Cntr=0.3,0.1

Type RM Length L Ch R = 1 ,3872    ,266.4,285.6,277.7
XS GIS Cut Line= 2
2022183.35974373296324.2920240422021785.28552163 296385.61998543
#Sta/Elev= 30
       0 1628.54    21.4  1627.9    34.7 1626.15   105.5 1606.14     121 1602.23
   124.3 1601.21   127.6 1599.43   134.2 1595.02   134.2 1594.97   137.6 1593.03
   140.9 1592.06   150.8 1591.57   157.5  1592.6   163.1  1595.6   167.4 1597.75
   170.8 1598.68   174.1 1599.05     193 1600.16   208.7 1600.33   253.7 1600.28
   279.4 1601.21   286.9 1601.09   293.6 1600.07   296.9  1600.4   306.9 1604.66
   313.5 1608.76   316.8 1609.74   346.7 1613.59     360 1615.69402.7707 1620.79
#Mann= 6 ,-1 , 0
       0    .016       0    21.4     .05       0   134.2    .045       0
   163.1     .05       0   208.7    .016       0   279.4     .05       0
Bank Sta=134.2,163.1
XS Rating Curve= 0 ,0
Exp/Cntr(USF)=0,0
Exp/Cntr=0.3,0.1

Type RM Length L Ch R = 1 ,3587    ,196.6,198.4,201
XS GIS Cut Line= 2
2022139.73888649296092.4029070312021748.16990993296138.289896472
#Sta/Elev= 30
       0 1623.08    20.3 1622.52    26.9 1621.63      50 1616.14    66.5 1612.85
   112.8 1600.87     126  1596.7   135.9 1594.47     159 1593.43   165.6 1593.97
   175.5 1593.23     202 1592.89   205.3 1592.03   211.9 1588.87   215.2 1587.65
   218.5 1587.29   238.3 1586.61   241.6 1586.87   244.9 1588.29   254.8 1595.22
   261.4 1596.16   275.2  1596.1   284.6 1595.26   287.9 1596.99   291.2 1599.63
   294.5 1601.55   317.6  1605.2   334.3 1609.23   360.9  1612.8394.2485 1614.79
#Mann= 6 ,-1 , 0
       0    .016       0    20.3     .05       0   211.9    .045       0
   244.9     .05       0   261.4    .016       0   275.2     .05       0
#Block Obstruct= 2 ,-1
  290.75   317.5 1625.18  360.69  394.25 1634.79
Bank Sta=211.9,244.9
XS Rating Curve= 0 ,0
Exp/Cntr(USF)=0,0
Exp/Cntr=0.3,0.1

Type RM Length L Ch R = 1 ,3388    ,217.5,220.9,219.7
XS GIS Cut Line= 3
2022099.97016231295927.2097450442021775.70210359295918.032347156
  2021714.519451295921.091479786
#Sta/Elev= 30
       0 1618.98    16.5 1618.24      23 1617.62    29.6  1616.3    98.5 1596.97
   128.1 1589.71   131.4 1589.17   141.2 1589.27   154.3 1587.91   170.7 1587.64
     180 1585.55   183.9  1584.5   190.4 1584.18   200.3 1584.41   206.6 1585.13
   213.4    1588   216.7 1588.71   236.4  1589.8   242.9 1591.44   247.6 1592.05
   267.3 1592.04   275.8 1591.98   285.6 1593.27   288.9 1595.09   292.2 1597.79
     296 1600.07     305 1604.44   318.4 1609.82   344.7 1613.24 385.657 1616.33
#Mann= 6 ,-1 , 0
       0    .016       0    16.5     .05       0     180    .045       0
   206.6     .05       0   247.6    .016       0   267.3     .05       0
#XS Ineff= 2 , 0
           144.9 1592.46  217.92         1591.46
Permanent Ineff=
       F       F
Bank Sta=180,206.6
XS Rating Curve= 0 ,0
Exp/Cntr(USF)=0,0
Exp/Cntr=0.3,0.1

Type RM Length L Ch R = 1 ,3167    ,275.7,275.8,271.2
XS GIS Cut Line= 3
2022070.90840233295696.2452315262021882.77174562295716.129593617
2021711.46031837295758.957450428
#Sta/Elev= 30
       0 1613.64    23.6 1612.91    30.2 1612.29    36.8 1610.16    49.8 1603.81
    66.5 1594.67    79.7 1589.24      83 1588.13    92.9  1586.5   108.8 1581.19
   112.7 1579.56   119.3 1579.15   129.2 1580.17   132.5 1581.46   139.1 1584.93
   142.4 1585.64   172.1 1584.85   229.2 1585.68   235.9 1586.38   242.7 1588.18
   249.4 1588.86   260.7 1588.79   310.3 1589.49   317.1 1590.48   320.5 1592.45
     334 1604.07   344.1 1609.61   347.5  1610.6   352.7 1611.17365.7683 1611.24
#Mann= 6 ,-1 , 0
       0    .016       0    23.6     .05       0   108.8    .045       0
   132.5     .05       0   249.4    .016       0   260.7     .05       0
#XS Ineff= 2 , 0
                           145.7         1588.02
Permanent Ineff=
       F       F
#Block Obstruct= 1 ,-1
  301.15  319.01 1611.54
Bank Sta=108.8,132.5
XS Rating Curve= 0 ,0
Exp/Cntr(USF)=0,0
Exp/Cntr=0.3,0.1

Type RM Length L Ch R = 1 ,2892    ,172.3,176,177.6
Node Name=A
XS GIS Cut Line= 3
2021992.90052028295419.3937285662021768.05427202295480.576381154
2021601.33154372295535.640768483
#Sta/Elev= 30
       0 1606.43     9.2 1605.81    25.1 1603.13    59.1 1592.33    86.3 1584.82
    96.5 1583.48   116.9  1582.2   130.5 1579.76   140.7 1576.52   144.1 1575.37
   154.3 1574.63   161.6 1574.97   167.9 1575.75   171.3 1576.66   178.1 1581.07
   184.9 1582.81   191.7 1583.46   202.4 1583.39   212.1 1584.02   225.7 1584.03
   277.4 1580.36   298.2  1579.8     312 1580.37   315.4 1581.22   324.6 1586.27
     335 1590.78   353.4 1596.98   363.8 1599.34   370.7  1600.2408.6024 1602.85
#Mann= 5 ,-1 , 0
       0     .05       0   140.7    .045       0   171.3     .05       0
   212.1    .016       0   225.7     .05       0
#XS Ineff= 2 , 0
                          218.87         1584.52
Permanent Ineff=
       F       F
#Block Obstruct= 1 ,-1
  268.86  308.56 1600.87
Bank Sta=140.7,171.3
XS Rating Curve= 0 ,0
Exp/Cntr(USF)=0,0
Exp/Cntr=0.3,0.1

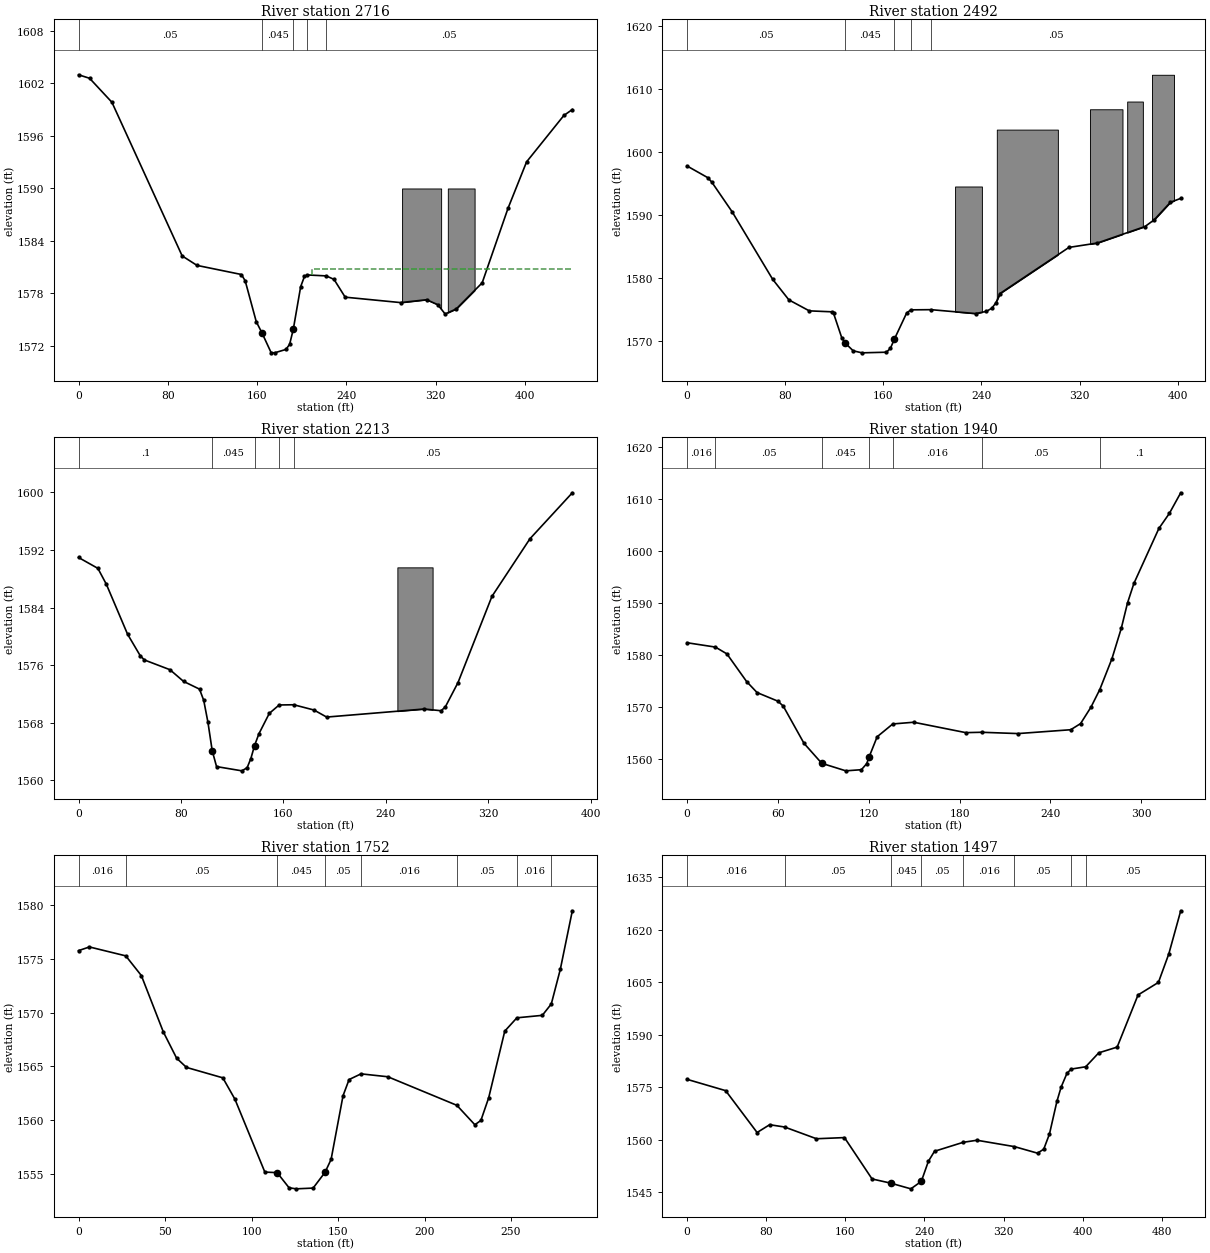
Type RM Length L Ch R = 1 ,2716    ,222.5,223.6,223.8
XS GIS Cut Line= 2
2021965.36832661295267.9666634112021527.91236061295335.267581258
#Sta/Elev= 30
       0 1602.99     9.9 1602.59    29.9 1599.85    92.9 1582.29   106.2 1581.21
     146 1580.17   149.4 1579.44   159.3 1574.78   164.6 1573.45   172.6 1571.25
   175.7 1571.22   185.9 1571.61   189.2 1572.19   192.5 1573.92   199.1 1578.78
   202.5 1579.95   204.9 1580.12   222.1 1580.01     229 1579.61     239 1577.58
   288.8 1576.96     312 1577.29     322 1576.72   328.6 1575.66   338.6 1576.24
   361.8 1579.22     385 1587.75   401.6 1593.04     435 1598.34442.6027 1599.02
#Mann= 5 ,-1 , 0
       0     .05       0   164.6    .045       0   192.5     .05       0
   204.9    .016       0   222.1     .05       0
#XS Ineff= 2 , 0
                           209.3         1580.77
Permanent Ineff=
       F       F
#Block Obstruct= 2 ,-1
     290     325    1590     331     355    1590
Bank Sta=164.6,192.5
XS Rating Curve= 0 ,0
Exp/Cntr(USF)=0,0
Exp/Cntr=0.3,0.1

Type RM Length L Ch R = 1 ,2492    ,279.4,279.2,279
XS GIS Cut Line= 2
2021913.36307191295055.3569456692021514.14626378295105.832634054
#Sta/Elev= 30
       0 1597.74      17 1595.87    20.3 1595.15    36.9 1590.43    69.9 1579.71
    83.1 1576.45    99.7 1574.71   117.9 1574.56   119.5 1574.31   126.1 1570.47
   129.2 1569.55   135.5 1568.36   142.7 1568.04   162.5 1568.14   165.8 1568.75
   169.1 1570.24     179 1574.35   182.4 1574.87   198.9  1574.9   235.2 1574.28
   244.1 1574.63   248.5 1575.14   251.8 1575.99   255.1 1577.46   311.3 1584.79
   334.5 1585.49   373.3 1588.11   380.8 1589.18     394 1591.96402.3951 1592.58
#Mann= 5 ,-1 , 0
       0     .05       0   129.2    .045       0   169.1     .05       0
   182.4    .016       0   198.9     .05       0
#Block Obstruct= 5 ,-1
   218.5  240.37 1594.47  252.52  302.28 1603.51  328.42  354.93 1606.74
  358.76  371.54 1607.97  378.97  396.89 1612.22
Bank Sta=129.2,169.1
XS Rating Curve= 0 ,0
Exp/Cntr(USF)=0,0
Exp/Cntr=0.3,0.1

Type RM Length L Ch R = 1 ,2213    ,277.5,273.3,270
XS GIS Cut Line= 2
 2021849.1212867294781.5645753392021466.72970802294832.040263723
#Sta/Elev= 30
       0 1590.97    15.1 1589.46    21.7 1587.26    38.3 1580.31    48.2 1577.32
    51.5 1576.73    71.4 1575.38      82 1573.76    94.5 1572.68    97.8 1571.11
   101.1 1568.05   104.4 1564.14   107.8 1561.92   127.6 1561.33   131.7 1561.77
   134.6 1563.04   137.5 1564.85   140.9 1566.48     149 1569.31   156.7 1570.48
   168.1 1570.51   183.9 1569.78   193.8  1568.8   269.9 1569.92   283.2 1569.68
   286.5 1570.21   296.4 1573.59   322.9 1585.56   352.6 1593.57385.7086 1599.96
#Mann= 5 ,-1 , 0
       0      .1       0   104.4    .045       0   137.5      .1       0
   156.7    .016       0   168.1     .05       0
#Block Obstruct= 1 ,-1
  249.05  276.56  1589.6
Bank Sta=104.4,137.5
XS Rating Curve= 0 ,0
Exp/Cntr(USF)=0,0
Exp/Cntr=0.3,0.1

Type RM Length L Ch R = 1 ,1940    ,187.5,188,186.8
XS GIS Cut Line= 2
2021786.40906779294495.5356744912021475.90710591294594.957484946
#Sta/Elev= 30
       0 1582.31    18.8 1581.47    26.4 1580.16    39.4 1574.84    46.3 1572.72
    60.1 1571.06    63.6 1570.11    77.3 1562.95      89 1559.11   104.9 1557.66
   115.2 1557.88   118.7 1559.05   120.3 1560.35   125.6 1564.22   135.9 1566.68
   149.7 1567.01   184.1 1565.01   194.5 1565.08   218.6 1564.83   253.4 1565.57
   259.9 1566.75   266.8 1569.93   272.6 1573.31   280.6 1579.22   286.8  1585.1
   290.9 1589.97   295.1 1593.71   311.6 1604.29   318.5 1607.18326.0309 1611.16
#Mann= 7 ,-1 , 0
       0    .016       0    18.8     .05       0      89    .045       0
   120.3     .05       0   135.9    .016       0   194.5     .05       0
   272.6      .1       0
Bank Sta=89,120.3
XS Rating Curve= 0 ,0
Exp/Cntr(USF)=0,0
Exp/Cntr=0.3,0.1

Type RM Length L Ch R = 1 ,1752    ,254.6,254.8,251.9
XS GIS Cut Line= 3
2021748.16990993294305.8694514692021654.86636473294341.049476707
2021478.96623854 294400.70256298
#Sta/Elev= 30
       0 1575.79     6.3 1576.13    27.3  1575.3    36.3 1573.47      49 1568.22
    56.7 1565.77    62.4 1564.91    83.4 1563.94    90.4 1561.95   107.7 1555.16
   114.8 1555.11   121.7  1553.7   125.8  1553.6   135.6 1553.67   142.5 1555.14
     146 1556.34   152.9 1562.27   156.4 1563.78   163.3 1564.31   178.8 1564.04
   218.7 1561.38   229.1 1559.57   232.6 1559.97   237.1 1562.08   246.4 1568.29
   253.4 1569.53   268.1 1569.76   273.3 1570.82   278.5 1574.04285.4555  1579.5
#Mann= 8 ,-1 , 0
       0    .016       0    27.3     .05       0   114.8    .045       0
   142.5     .05       0   163.3    .016       0   218.7     .05       0
   253.4    .016       0   273.3     .05       0
Bank Sta=114.8,142.5
XS Rating Curve= 0 ,0
Exp/Cntr(USF)=0,0
Exp/Cntr=0.3,0.1

Type RM Length L Ch R = 1 ,1497    ,278.1,278.6,273.8
XS GIS Cut Line= 2
2021735.93337941294038.1953463972021272.47478606294223.272870475
#Sta/Elev= 30
       0 1577.26    39.1 1574.02    70.9 1562.06    83.6 1564.29    98.7 1563.63
   130.9 1560.28   159.2 1560.61   187.1 1548.79   205.9  1547.6   226.3 1545.97
   236.9 1548.11     244 1553.83   250.2  1556.7   279.3 1559.27   293.1 1559.85
     331 1558.03   354.3 1556.16   360.6  1557.3   366.4 1561.65   373.9 1570.95
   378.2 1575.05     384 1578.92   388.2 1580.17     403 1580.84   416.2 1584.82
   434.8 1586.46   455.9 1601.35   476.5 1604.94     487 1613.08499.0467  1625.4
#Mann= 8 ,-1 , 0
       0    .016       0    98.7     .05       0   205.9    .045       0
   236.9     .05       0   279.3    .016       0     331     .05       0
   388.2    .016       0     403     .05       0
Bank Sta=205.9,236.9
XS Rating Curve= 0 ,0
Exp/Cntr(USF)=0,0
Exp/Cntr=0.5,0.3

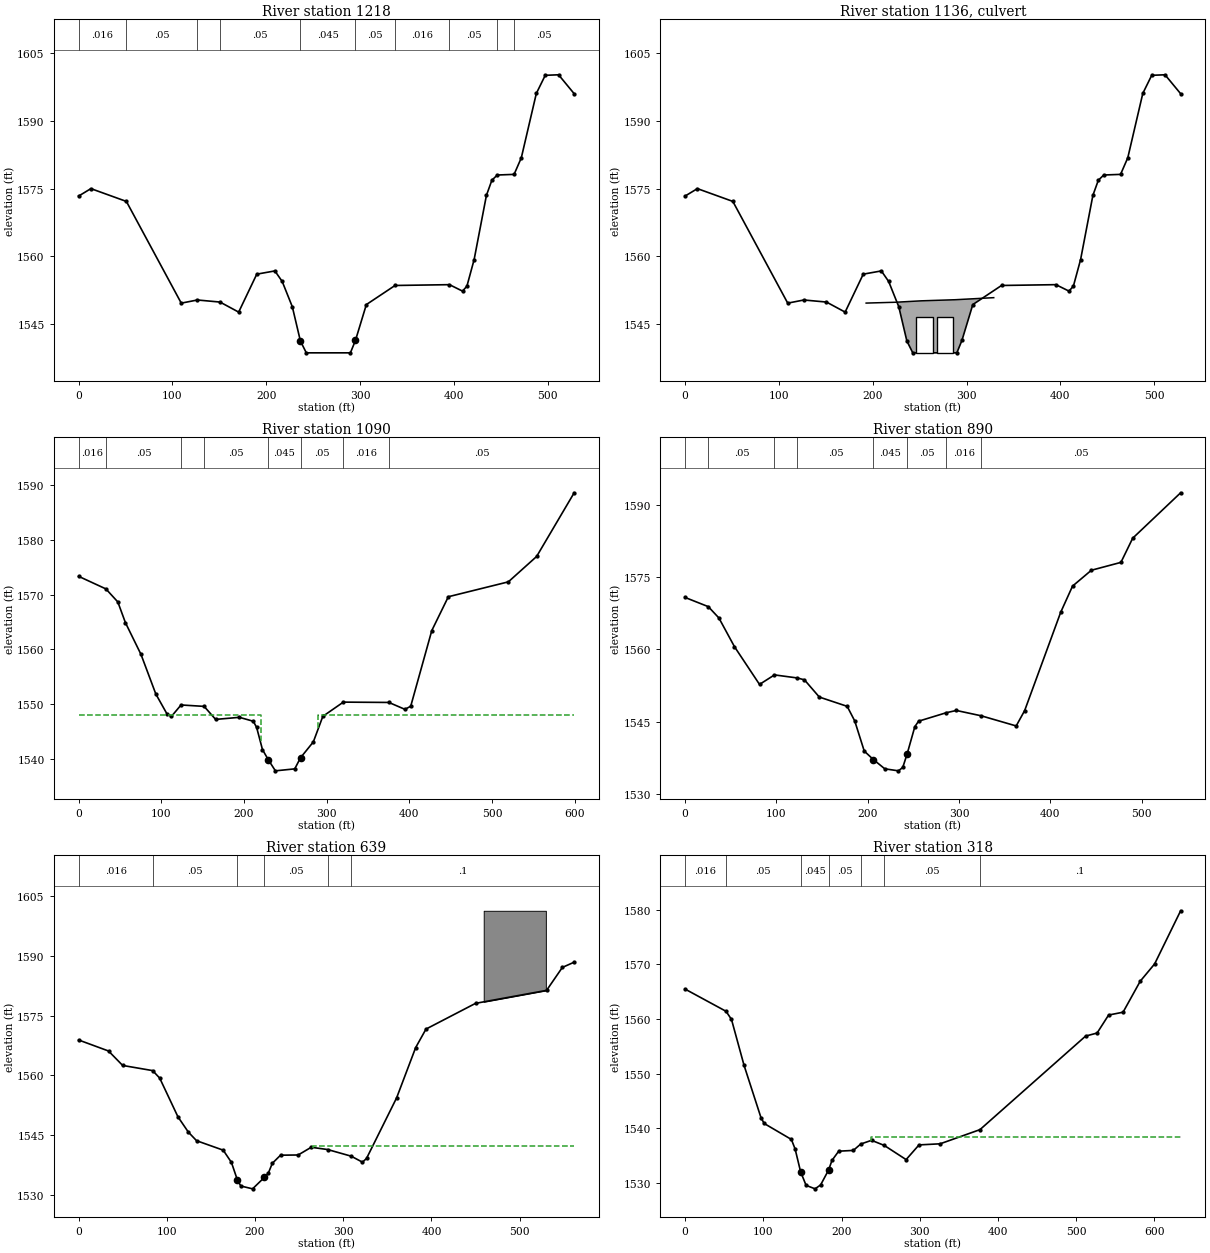
Type RM Length L Ch R = 1 ,1218    ,129,128.1,124.1
XS GIS Cut Line= 4
2021639.92381907293794.1830318662021440.59761894293857.128147697
2021346.17994519293907.4842403612021199.30800825294060.650688884
#Sta/Elev= 30
       0 1573.33    13.1 1574.98    50.9 1572.14   109.4 1549.57   126.6 1550.27
   150.7 1549.81   170.6 1547.58   189.9    1556   209.2 1556.72     217 1554.38
   227.8 1548.76   236.4 1541.17   242.71538.543   289.71538.543   295.1  1541.3
   306.7 1549.25   337.3 1553.49   395.3 1553.67   409.2 1552.24   413.9 1553.33
   421.6 1559.24   434.7 1573.48   440.5 1576.84   446.3    1578   464.2 1578.14
   471.9 1581.82   487.9  1596.1   497.4 1600.12   511.6 1600.24528.2413 1596.04
#Mann= 10 ,-1 , 0
       0    .016       0    50.9     .05       0   126.6    .016       0
   150.7     .05       0   236.4    .045       0   295.1     .05       0
   337.3    .016       0   395.3     .05       0   446.3    .016       0
   464.2     .05       0
#XS Ineff= 2 , 0
             214 1549.79     318         1550.61
Permanent Ineff=
       F       F
Bank Sta=236.4,295.1
XS Rating Curve= 0 ,0
Exp/Cntr(USF)=0,0
Exp/Cntr=0.5,0.3

Type RM Length L Ch R = 2 ,1136    ,,,
BEGIN DESCRIPTION:
County Route 4
Survey ID: LIC100
END DESCRIPTION:
Bridge Culvert--1,0,-1,-1, 0
Deck Dist Width WeirC Skew NumUp NumDn MinLoCord MaxHiCord MaxSubmerge Is_Ogee
70,40,2.6,0, 5, 6, , , 0.98, 0, 0,0,,
     193     224     252     288     329
1549.5831549.7661550.087 1550.331550.785
                                        
     150     193     224     252     288     329
1549.5831549.5831549.7661550.087 1550.331550.785
                                                
BR Coef=-1 , 1 , 0 ,, 0 ,,,0.8,0,1.2,0,
WSPro=,,,, 1 ,,,, 0 ,,,, 0 ,,,,-1 ,-1 ,-1 , 0 , 0 , 0 , 0 , 0
Culvert=2,8,18,78,0.012,0.4,1,8,1,1538.543,255,1537.857,240,Culvert #1  , 0 ,32
     255     240
BC Culvert Barrel=1,Barrel 1,0
Culvert Bottom n=0.012
Culvert=2,8,18,78,0.012,0.4,1,8,1,1538.605,277,1537.819,262,Culvert #2  , 0 ,32
     277     262
BC Culvert Barrel=1,Barrel 1,0
Culvert Bottom n=0.012
BC Design=,, 0 ,, 0 ,,,,,,
BC Use User HTab Curves=0
BC User HTab FreeFlow(D)= 0

Type RM Length L Ch R = 1 ,1090    ,201.7,200.4,197.9
XS GIS Cut Line= 4
2021512.63480706293607.2127248422021388.14335575 293735.43425709
2021295.82385253293794.1830318662021027.25802498293951.545821443
#Sta/Elev= 30
       0 1573.36      33 1571.06    47.4 1568.68    56.6 1564.89    75.4  1559.1
    93.4 1551.84   107.1 1548.15   112.3 1547.77   123.9 1549.85   151.8 1549.59
   165.7 1547.21   194.5 1547.59   211.3 1546.87   215.3 1545.75   222.4 1541.68
   229.5 1539.82  238.01 1537.81   261.4 1538.17   268.4  1540.2   283.9  1543.1
   295.4 1547.77   320.2 1550.37   375.3 1550.31   394.7 1549.05   401.7 1549.62
   427.2 1563.45   447.2 1569.63   519.8 1572.35     554 1576.99599.4144 1588.63
#Mann= 8 ,-1 , 0
       0    .016       0      33     .05       0   123.9    .016       0
   151.8     .05       0   229.5    .045       0   268.4     .05       0
   320.2    .016       0   375.3     .05       0
#XS Ineff= 2 , 0
             220    1548     290            1548
Permanent Ineff=
       F       F
Bank Sta=229.5,268.4
XS Rating Curve= 0 ,0
Exp/Cntr(USF)=0,0
Exp/Cntr=0.5,0.3

Type RM Length L Ch R = 1 ,890     ,253.1,250.8,248.7
XS GIS Cut Line= 2
 2021391.7809586 293475.314942592020958.91369154293802.642133934
#Sta/Elev= 30
       0 1570.81    25.4  1568.9      37 1566.55    54.1 1560.56    81.5 1552.72
    97.9  1554.7     123 1554.06   130.7 1553.67     147 1550.09   177.5 1548.16
   185.8 1545.11   196.2 1538.85   206.3 1537.07   218.7 1535.16   233.7 1534.74
   238.4 1535.46   243.1 1538.22   251.6 1543.93   255.7 1545.07   286.2 1546.84
   297.1  1547.3   324.3 1546.19   362.6 1544.08   371.9 1547.29   411.3 1567.71
   424.3 1573.17   444.9 1576.47   477.3 1578.11   490.2 1583.14542.6943 1592.59
#Mann= 8 ,-1 , 0
       0    .016       0    25.4     .05       0    97.9    .016       0
     123     .05       0   206.3    .045       0   243.1     .05       0
   286.2    .016       0   324.3     .05       0
Bank Sta=206.3,243.1
XS Rating Curve= 0 ,0
Exp/Cntr(USF)=0,0
Exp/Cntr=0.3,0.1

Type RM Length L Ch R = 1 ,639     ,323.4,321.1,318.9
XS GIS Cut Line= 3
2021205.17386821293279.5304543092020981.85718626293484.492340478
2020805.95706007  293674.1585635
#Sta/Elev= 30
       0 1568.88    33.9 1566.11    49.9 1562.48    83.9 1561.18    91.9  1559.3
   112.6 1549.56   124.4 1545.72   133.7 1543.56   163.9 1541.18   173.2 1538.12
   180.1 1533.61   183.9 1532.17   197.2 1531.46   210.6 1534.34     215 1535.38
   219.6 1537.88   228.9 1539.92   248.9 1539.97   263.7 1541.91   282.3 1541.34
     309 1539.67   321.8 1538.16   326.4 1539.11   360.5 1554.33   382.1 1566.97
   393.8 1571.62     450 1578.09   530.5 1581.35   548.4 1587.12561.7943 1588.44
#Mann= 6 ,-1 , 0
       0    .016       0    83.9     .05       0   180.1    .045       0
   210.6     .05       0   282.3    .016       0     309      .1       0
#XS Ineff= 2 , 0
                          266.03         1542.16
Permanent Ineff=
       F       F
#Block Obstruct= 1 ,-1
  459.23  529.69 1601.36
Bank Sta=180.1,210.6
XS Rating Curve= 0 ,0
Exp/Cntr(USF)=0,0
Exp/Cntr=0.3,0.1

Type RM Length L Ch R = 1 ,318     ,311.2,317.8,307.9
XS GIS Cut Line= 4
2020922.20409999293082.2163997132020755.48137169293276.471321679
2020649.94129598 293449.312315242020570.40384761293605.328079339
#Sta/Elev= 30
       0 1565.46    52.3  1561.4    59.3 1559.92    75.4  1551.5      97 1541.95
   101.1 1540.87   135.9 1537.95   140.7 1536.19   147.7 1532.03   154.7 1529.55
   166.2 1528.91   173.3 1529.63   183.5 1532.36   187.8 1534.11   196.4  1535.8
   215.1 1535.94   224.5  1537.1   238.4 1537.79   254.7 1536.85   282.6 1534.26
   299.1 1536.95   326.1 1537.15     377 1539.74   512.1 1556.86   526.8 1557.42
   541.5 1560.71     560 1561.23     582 1566.91   600.4 1570.07633.6274 1579.79
#Mann= 7 ,-1 , 0
       0    .016       0    52.3     .05       0   147.7    .045       0
   183.5     .05       0   224.5    .016       0   254.7     .05       0
     377      .1       0
#XS Ineff= 2 , 0
                          237.41         1538.32
Permanent Ineff=
       F       F
Bank Sta=147.7,183.5
XS Rating Curve= 0 ,0
Exp/Cntr(USF)=0,0
Exp/Cntr=0.3,0.1

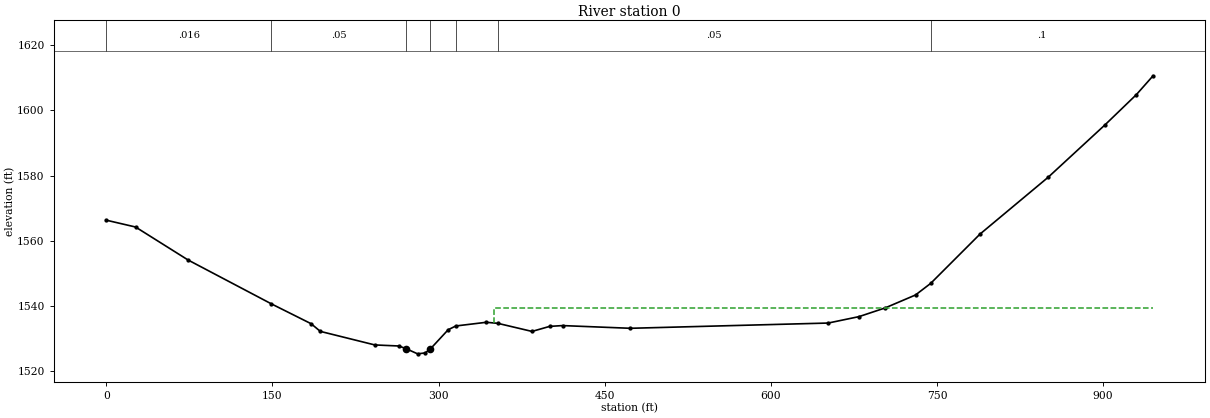
Type RM Length L Ch R = 1 ,0       ,0,0,0
XS GIS Cut Line= 5
2020753.74531356292905.8149460472020604.76919724293006.213471919
2020529.09900004293065.3600000142020483.73576711293207.264514908
2020334.54112618293705.810566112
#Sta/Elev= 30
       0 1566.31    26.5 1564.21    73.9 1554.09   149.1 1540.63     185 1534.53
   193.3 1532.18   242.5 1528.02   264.1  1527.7   270.5 1526.91   281.1 1525.29
     288 1525.57   292.7 1526.81   308.7 1532.68   315.6 1533.84   343.1 1534.97
   353.4 1534.66   384.4 1532.17   400.4 1533.72     412 1533.96   473.2 1533.13
   651.8 1534.74   679.6 1536.71   703.2 1539.38   730.6 1543.35   744.3 1546.91
   788.8 1562.03   850.4 1579.49   901.8  1595.6     930 1604.84945.0624 1610.62
#Mann= 7 ,-1 , 0
       0    .016       0   149.1     .05       0   270.5    .045       0
   292.7     .05       0   315.6    .016       0   353.4     .05       0
   744.3      .1       0
#XS Ineff= 2 , 0
                          350.42         1539.35
Permanent Ineff=
       F       F
Bank Sta=270.5,292.7
XS Rating Curve= 0 ,0
Exp/Cntr(USF)=0,0
Exp/Cntr=0.3,0.1
LCMann Table=0

Chan Stop Cuts=-1
Use User Specified Reach Order=0
Composite Channel Slope=5